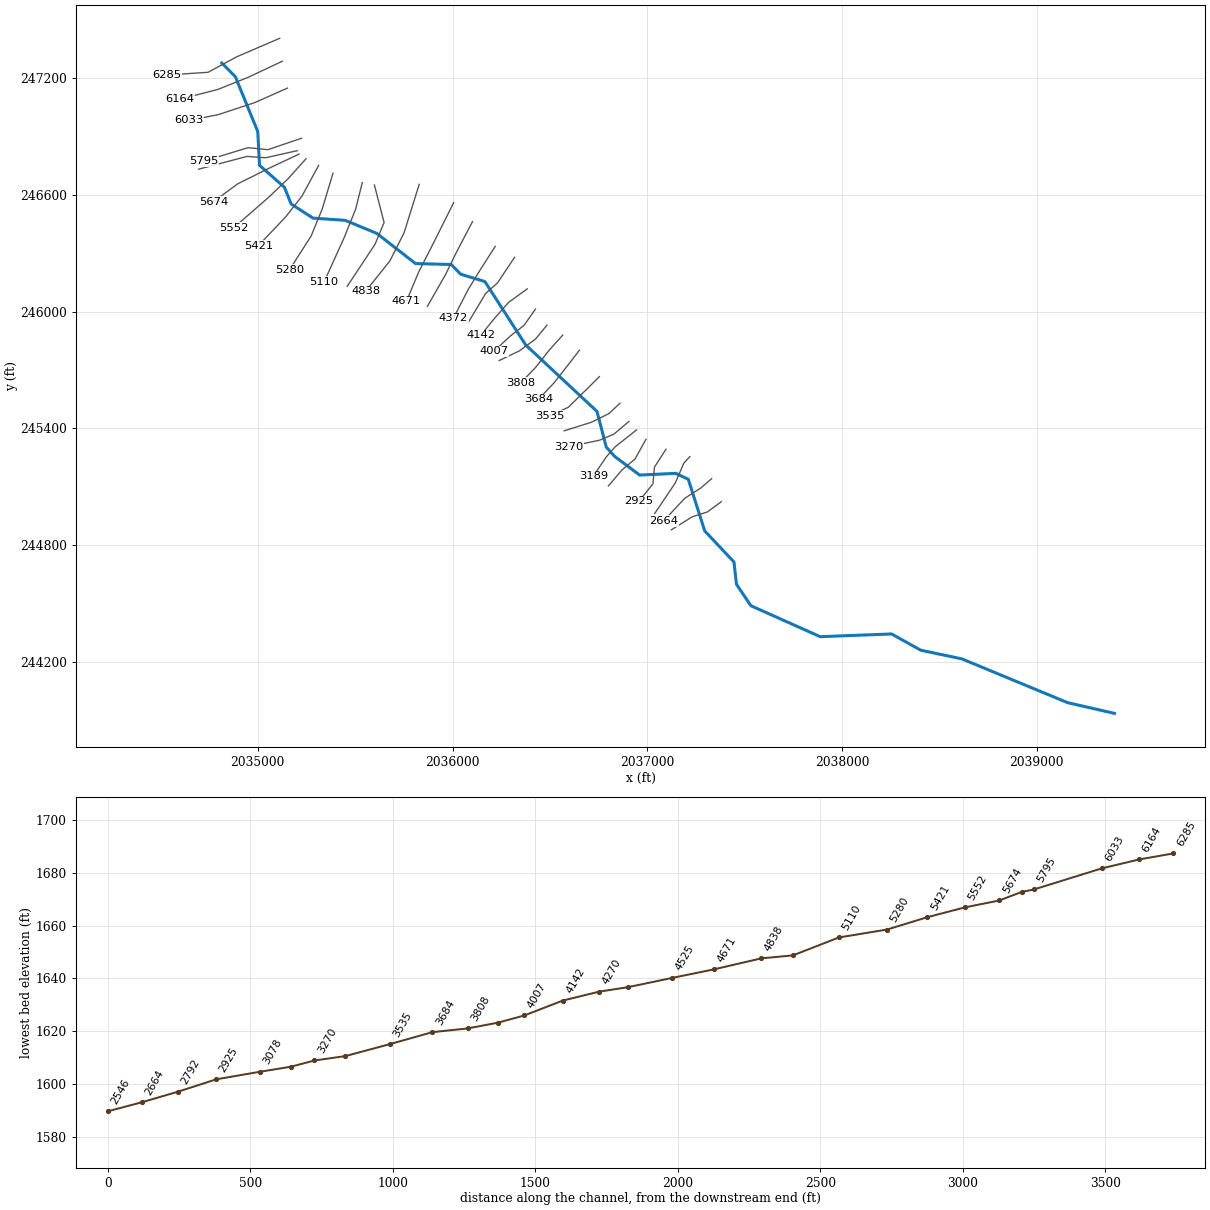
--- BOONECK.prj (project) ---

Proj Title=BOONECK
Current Plan=p01
Default Exp/Contr=0,0
English Units
Geom File=g01
Flow File=f01
Plan File=p01
BEGIN DESCRIPTION:
Stream Name: Boone Creek
Flood Zone: Approximate
Summers County, West Virginia
HEC-RAS Version: 5.0.7
Hydrology Method:
Regression.
Model Notes:
END DESCRIPTION:
DSS Export Rating Curves= 0
DSS Export Rating Curve Sorted= 0
DSS Export Volume Flow Curves= 0
DXF OffsetX= 0
DXF OffsetY= 0
DXF ScaleX= 0
DXF ScaleY= 0

--- BOONECK.p01 (plan) ---

Plan Title=Floodplain
Program Version=5.07
Short Identifier=Floodplain
Geom File=g01
Flow File=f01
Subcritical Flow
K Sum by GR= 0
Std Step Tol= 0.01
Critical Tol= 0.01
Num of Std Step Trials= 20
Max Error Tol= 0.3
Flow Tol Ratio= 0.001
Split Flow NTrial= 30
Split Flow Tol= 0.02
Split Flow Ratio= 0.02
Log Output Level= 0
Friction Slope Method= 1
Unsteady Friction Slope Method= 2
Unsteady Bridges Friction Slope Method= 1
Parabolic Critical Depth
Global Vel Dist= 0 , 0 , 0
Global Log Level= 0
CheckData=True
Encroach Param=-1 ,0,0, 0
Mapping Interval=1HOUR
Computation Time Step Use Courant=        0
Computation Time Step Use Time Series=    0
Computation Time Step Count To Double=0
Computation Time Step Max Doubling=0
Computation Time Step Max Halving=0
Computation Time Step Residence Courant=0
Run HTab= 0
Run UNet= 0
Run Sediment= 0
Run PostProcess= 0
Run WQNet= 0
Run RASMapper= 0
UNET Theta= 0
UNET Theta Warmup= 0
UNET ZTol= 0
UNET ZSATol= 0
UNET MxIter= 0
UNET Max Iter WO Improvement= 0
UNET MaxInSteps= 0
UNET DtIC= 0
UNET DtMin= 0
UNET MaxCRTS= 0
UNET WFStab= 0
UNET SFStab= 0
UNET WFX= 1
UNET SFX= 1
UNET 1D Methodology=Finite Difference
UNET DSS MLevel= 1
UNET Pardiso=0
UNET DZMax Abort= 0
UNET Use Existing IB Tables= 0
UNET Froude Reduction=False
UNET Froude Limit= 0
UNET Froude Power= 0
UNET D1 Cores= 0
UNET D2 Coriolis=0
UNET D2 Cores= 0
UNET D2 Theta= 1
UNET D2 Theta Warmup= 1
UNET D2 Z Tol= 0.01
UNET D2 Volume Tol= 0.01
UNET D2 Max Iterations= 20
UNET D2 Equation= 0
UNET D2 RampUpFraction=0.1
UNET D2 TimeSlices= 1
UNET D2 BCVolumeCheck=0
UNET D1D2 MaxIter= 0
UNET D1D2 ZTol=0.01
UNET D1D2 QTol=0.1
UNET D1D2 MinQTol=1
Write IC File= 0
Write IC File at Fixed DateTime=0
Write IC File at Sim End=0
Echo Input=False
Echo Parameters=False
Echo Output=False
Write Detailed= 0
HDF Write Warmup=0
HDF Write Time Slices=0
HDF Flush=0
HDF Face Node Velocities=0
HDF Compression= 1
HDF Chunk Size= 1
HDF Spatial Parts= 1
HDF Use Max Rows=0
HDF Fixed Rows= 1
Calibration Method= 0
Calibration Iterations= 20
Calibration Max Change=0.05
Calibration Tolerance=0.2
Calibration Maximum=1.5
Calibration Minimum=0.5
Calibration Optimization Method= 1
WQ AD Non Conservative
WQ ULTIMATE=-1
WQ Max Comp Step=1HOUR
WQ Output Interval=15MIN
WQ Output Selected Increments= 0
WQ Output face flow=0
WQ Output face velocity=0
WQ Output face area=0
WQ Output face dispersion=0
WQ Output cell volume=0
WQ Output cell surface area=0
WQ Output cell continuity=0
WQ Output cumulative cell continuity=0
WQ Output face conc=0
WQ Output face dconc_dx=0
WQ Output face courant=0
WQ Output face peclet=0
WQ Output face adv mass=0
WQ Output face disp mass=0
WQ Output cell mass=0
WQ Output cell source sink temp=0
WQ Output nsm pathways=0
WQ Output nsm derived pathways=0
WQ Output MaxMinRange=-1
WQ Daily Max Min Mean=-1
WQ Daily Range=0
WQ Daily Time=0
WQ Create Restart=0
WQ Fixed Restart=0
WQ System Summary=0
WQ Write To DSS=0
WQ Use Fixed Temperature=0
Sorting and Armoring Iterations= 10
XS Update Threshold= 0.02
Bed Roughness Predictor= 0
Hydraulics Update Threshold= 0.02
Energy Slope Method= 1
Volume Change Method= 1
Sediment Retention Method= 0
XS Weighting Method= 0
Number of US Weighted Cross Sections= 1
Number of DS Weighted Cross Sections= 1
Upstream XS Weight=0
Main XS Weight=1
Downstream XS Weight=0
Number of DS XS's Weighted with US Boundary= 1
Upstream Boundary Weight= 1
Weight of XSs Associated with US Boundary= 0
Number of US XS's Weighted with DS Boundary= 1
Downstream Boundary Weight= 0.5
Weight of XSs Associated with DS Boundary= 0.5
Percentile Method= 0
Sediment Output Level= 3
Mass or Volume Output= 0
Output Increment Type= 1
Profile and TS Output Increment= 1
XS Output Flag= 0
XS Output Increment= 10
Write Gradation File= 0
Read Gradation Hotstart= 0
Write HDF5 File= 1
Write Binary Output= 1
Write DSS Sediment File= 0
SV Curve= 0
Specific Gage Flag= 0

--- BOONECK.f01 (steady flow) ---

Flow Title=Flows
Program Version=5.07
Number of Profiles= 6
Profile Names=01pct,10pct,04pct,02pct,0_2pct,01plus
River Rch & RM=BOONECK,Main            ,6285
     516     271     362     436     722     763
River Rch & RM=BOONECK,Main            ,5674
     662     352     466     561     922     979
River Rch & RM=BOONECK,Main            ,1717
     788     421     557     669    1094    1165
Boundary for River Rch & Prof#=BOONECK,Main            , 1
Up Type= 0
Dn Type= 3
Dn Slope=0.07463
Boundary for River Rch & Prof#=BOONECK,Main            , 2
Up Type= 0
Dn Type= 3
Dn Slope=0.07463
Boundary for River Rch & Prof#=BOONECK,Main            , 3
Up Type= 0
Dn Type= 3
Dn Slope=0.07463
Boundary for River Rch & Prof#=BOONECK,Main            , 4
Up Type= 0
Dn Type= 3
Dn Slope=0.07463
Boundary for River Rch & Prof#=BOONECK,Main            , 5
Up Type= 0
Dn Type= 3
Dn Slope=0.07463
Boundary for River Rch & Prof#=BOONECK,Main            , 6
Up Type= 0
Dn Type= 3
Dn Slope=0.07463
DSS Import GetInterval= 0
DSS Import GetPeak= 0
DSS Import FillOption= 0

--- BOONECK.g01 (geometry) ---

Geom Title=Geometry
Program Version=5.07

River Reach=BOONECK         ,Main
Reach XY= 30
     2034815.435      247275.947     2034884.873      247205.889
      2035000.15      246923.332     2035009.089      246750.616
     2035137.012      246637.989     2035171.244      246552.238
     2035283.484        246479.5      2035448.83      246468.142
     2035611.262      246401.028     2035809.873      246246.167
     2035993.206      246241.305     2036042.512      246191.306
     2036166.123      246153.805     2036375.845      245828.111
     2036741.867      245486.894     2036789.561      245303.458
     2036832.963      245255.715     2036960.568      245160.229
      2037146.07      245168.991     2037210.568      245138.528
     2037294.769      244873.771     2037444.943      244714.048
     2037457.963      244599.465     2037531.847      244489.517
     2037887.706      244330.351     2038254.531      244344.353
     2038404.373      244260.906     2038615.688        244216.3
     2039158.373      243991.551       2039398.7       243936.62

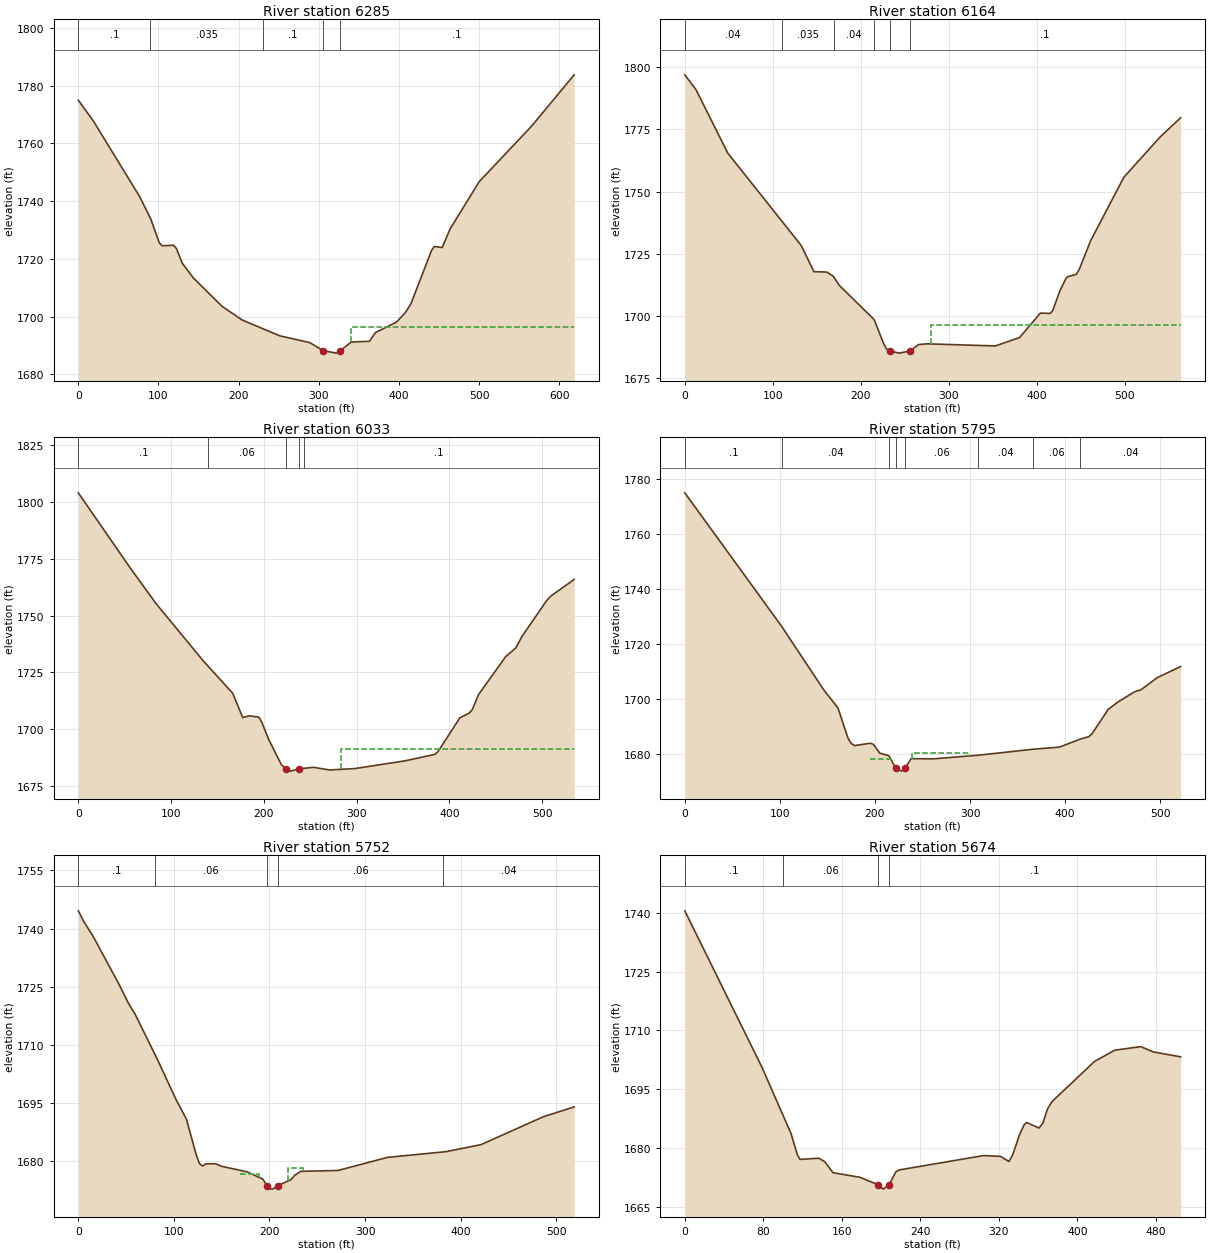
Type RM Length L Ch R = 1 ,6285    ,122.7,120.4,118.9
XS GIS Cut Line= 4
2035112.60623248247402.5567364912034891.52880447247307.562529139
2034744.71957492247228.1128284462034534.00515134247214.295489194
#Sta/Elev= 30
       0 1774.95    18.9 1767.69    76.6 1741.54    90.3 1733.89     101 1725.59
   104.6 1724.56   118.8 1724.74   122.4 1723.62   129.6 1718.53   143.8 1713.34
   179.5 1703.56   204.5 1698.85   251.4 1693.38   288.7 1691.04  305.641688.234
   322.3 1687.39  326.821688.233   340.6 1691.24   363.3 1691.48   370.8 1694.52
   396.9 1698.12     408  1701.4   414.8 1704.33   440.9 1723.02   444.2 1724.31
   454.1 1723.95   463.9 1730.39   500.1 1746.71     566  1766.1   618.7 1783.74
#Mann= 5 ,-1 , 0
       0      .1       0      90    .035       0     230      .1       0
  305.64    .045       0  326.82      .1       0
#XS Ineff= 2 , 0
                          339.97         1696.47
Permanent Ineff=
       F       F
Bank Sta=305.64,326.82
XS Rating Curve= 0 ,0
Exp/Cntr(USF)=0,0
Exp/Cntr=0.3,0.1

Type RM Length L Ch R = 1 ,6164    ,133.1,131.3,130.4
XS GIS Cut Line= 4
2035126.42357173247285.1093528562034950.25249628 247202.20531735
2034794.80742971 247140.027290722034599.63751279247089.939435935
#Sta/Elev= 30
       0 1796.94    12.7    1791    48.9 1765.45   132.3 1728.38   146.8 1717.83
   161.3 1717.69   168.6 1716.06   175.8 1712.26   215.2  1698.6   225.8 1689.09
   229.3 1686.82  233.431685.931   243.5  1685.1  255.651685.931   265.6 1688.52
   275.3 1688.84     353 1687.99   380.5 1691.34   404.2 1701.18   415.4 1701.07
   418.1 1702.11   426.2 1709.94   432.8  1714.8   434.7 1715.78   444.8 1716.72
   448.2  1718.6   461.2 1730.18     499 1755.75   540.1 1771.89   563.6  1779.7
#Mann= 6 ,-1 , 0
       0     .04       0     110    .035       0     170     .04       0
   214.7      .1       0  233.43    .045       0  255.65      .1       0
#XS Ineff= 2 , 0
                          280.23         1696.47
Permanent Ineff=
       F       F
Bank Sta=233.43,255.65
XS Rating Curve= 0 ,0
Exp/Cntr(USF)=0,0
Exp/Cntr=0.3,0.1

Type RM Length L Ch R = 1 ,6033    ,243.6,237.7,230.9
XS GIS Cut Line= 4
2035152.33108283247146.9359603452034984.79584441247072.667761871
2034796.53459711247010.4897352412034646.27103276246981.127889332
#Sta/Elev= 30
       0 1803.87    55.2 1771.32    83.9 1755.21   134.2 1730.34   166.5 1715.86
   177.2 1705.23   184.4 1705.97   194.7  1705.4   198.2 1702.81   205.1 1695.74
   218.9 1684.54  224.191682.511   229.3  1681.7   237.4 1682.65   253.5 1683.38
   270.8 1682.21   298.4 1682.84   352.5 1686.23   384.7  1689.1     388 1690.39
   411.4 1705.13   421.4 1707.15   424.8  1708.7   431.5 1715.29   460.7 1731.93
   471.6 1735.73   478.3  1740.8     505 1756.61   509.6  1758.6   534.6 1765.83
#Mann= 5 ,-1 , 0
       0      .1       0     140     .06       0  224.19    .045       0
   237.4     .06       0  243.26      .1       0
#XS Ineff= 2 , 0
                          282.81         1691.25
Permanent Ineff=
       F       F
Bank Sta=224.19,237.4
XS Rating Curve= 0 ,0
Exp/Cntr(USF)=0,0
Exp/Cntr=0.5,0.3

Type RM Length L Ch R = 1 ,5795    ,43.1,43.6,44
XS GIS Cut Line= 4
 2035224.8721139246889.5880167942035052.15537326246830.864324976
2034950.25249628246841.2273294152034723.99356605246772.140633159
#Sta/Elev= 30
       0  1775.1   102.2 1726.31   102.2 1726.28   102.2 1726.27   146.2  1703.3
   161.1 1696.72   171.5 1685.85     175 1683.81   178.5 1683.05   195.1 1683.88
   198.4 1683.46     205 1680.29   214.6 1679.36  221.691674.916   228.1 1673.73
  231.851674.917     238 1678.28   261.1  1678.2   308.2 1679.51   366.4 1681.71
   393.9 1682.47   415.8 1685.39   424.8 1686.29   428.2 1687.31   445.3 1696.24
   455.3 1698.87   472.8 1702.59   479.7 1703.35   496.8 1707.79   521.4 1711.82
#Mann= 8 ,-1 , 0
       0      .1       0   102.2     .04       0   214.6     .06       0
  221.69    .045       0  231.85     .06       0   308.2     .04       0
   366.4     .06       0   415.8     .04       0
#XS Ineff= 2 ,-1
  194.27  216.62  1678.2  238.97  299.14 1680.47
Permanent Ineff=
       F       F
Bank Sta=221.69,231.85
XS Rating Curve= 0 ,0
Exp/Cntr(USF)=0,0
Exp/Cntr=0.5,0.3

Type RM Length L Ch R = 1 ,5752    ,69.2,78,85.8
XS GIS Cut Line= 4
2035202.41893762246825.6828227572035040.06520141246789.412307223
2034945.07099406246796.3209768492034696.35888754246730.688615406
#Sta/Elev= 30
       0 1744.58     5.6 1741.87    15.7  1737.9    42.5 1725.66    52.6 1720.65
    59.4 1717.92      83  1706.1   102.2  1695.9   113.1 1690.82   123.2 1681.76
   126.6 1679.41     130 1678.72   133.3 1679.28   143.4 1679.32   150.1 1678.64
   176.8 1677.21     193 1675.36  197.471673.647   199.8 1672.87   203.1 1672.76
  208.641673.647   222.8 1675.25   226.1 1676.27   232.7 1677.35   271.8 1677.58
   323.4 1680.95   384.6 1682.43   421.2 1684.23   486.6 1691.44   518.8 1693.98
#Mann= 5 ,-1 , 0
       0      .1       0      80     .06       0  197.47    .045       0
  208.64     .06       0   381.6     .04       0
#XS Ineff= 2 ,-1
  169.43   189.21676.745   219.2  235.53 1678.16
Permanent Ineff=
       F       F
Bank Sta=197.47,208.64
XS Rating Curve= 0 ,0
Exp/Cntr(USF)=0,0
Exp/Cntr=0.5,0.3

Type RM Length L Ch R = 1 ,5674    ,116.9,121.4,124.6
XS GIS Cut Line= 4
2035212.23173446246808.1705637042035065.02092541246739.026092783
2034897.73591512246655.7553321052034772.08628516 246563.56270421
#Sta/Elev= 30
       0 1740.49    78.6 1700.63   108.2 1683.77   114.7  1678.3   117.4 1677.13
   136.5 1677.43   142.7 1676.55     151 1673.74   178.3 1672.58   197.21670.652
   202.1 1669.55  208.251670.652   215.1 1673.98   218.7 1674.45   304.3  1678.1
   321.5 1677.91   330.4  1676.6   334.1 1678.26     341 1683.34   345.9 1685.99
   348.4 1686.54   360.9 1685.12   364.9 1686.32   369.5 1689.92   374.2 1691.86
   417.8 1702.15   438.2 1704.96   464.6 1705.88   477.5 1704.52   505.3 1703.28
#Mann= 4 ,-1 , 0
       0      .1       0     100     .06       0   197.2    .045       0
  208.25      .1       0
Bank Sta=197.2,208.25
XS Rating Curve= 0 ,0
Exp/Cntr(USF)=0,0
Exp/Cntr=0.3,0.1

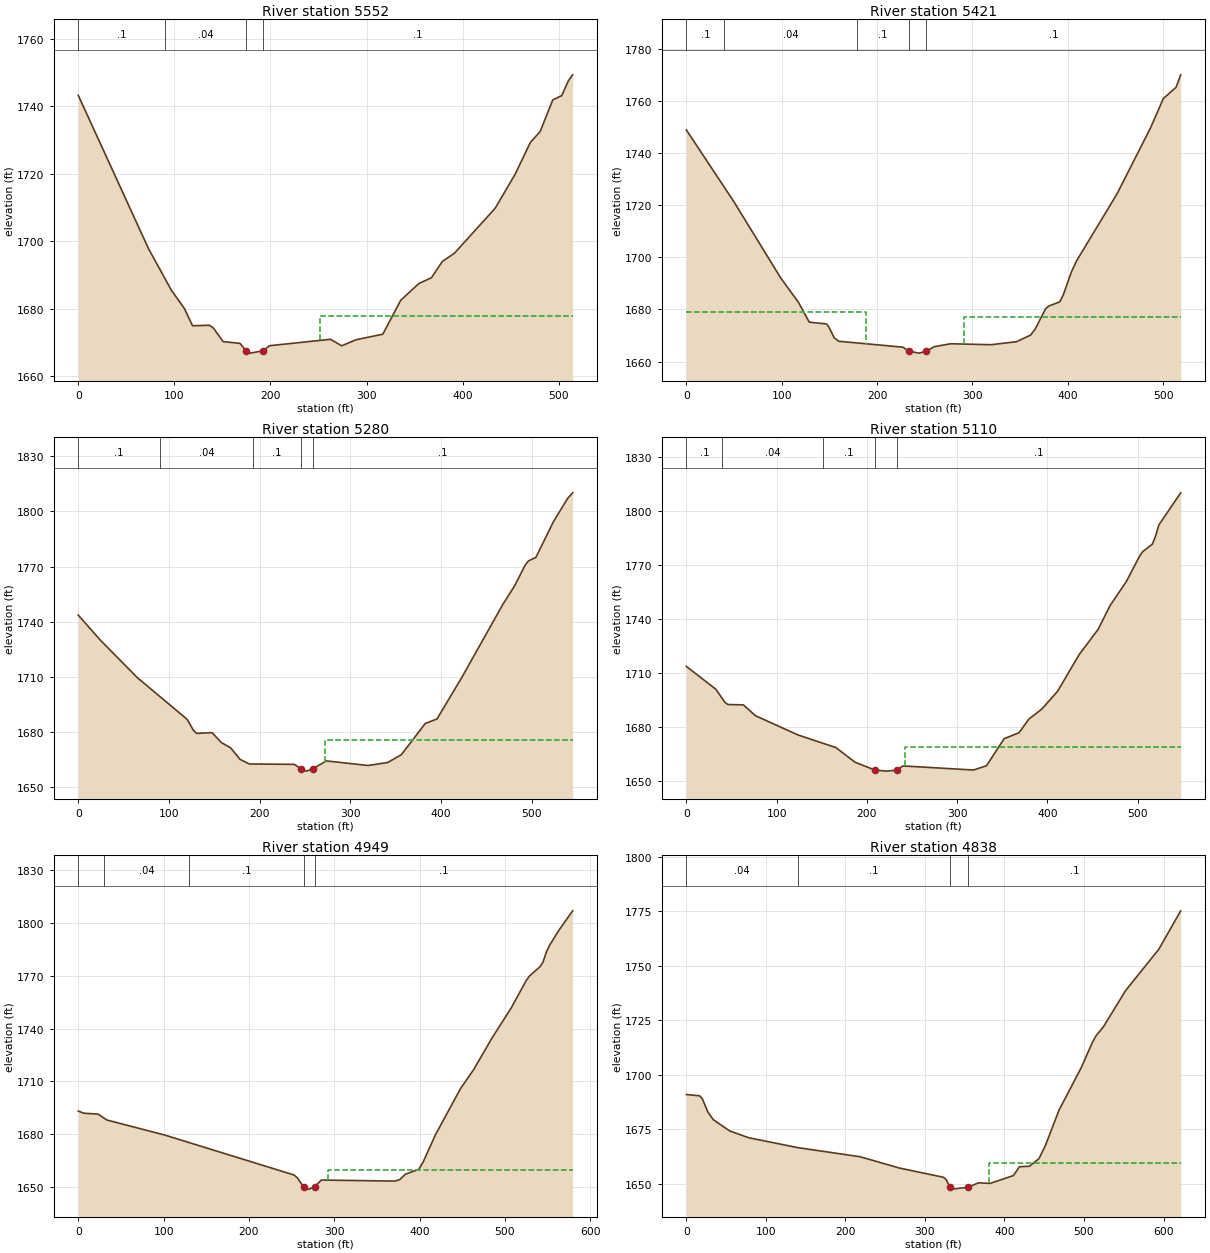
Type RM Length L Ch R = 1 ,5552    ,125.8,130.8,131.8
XS GIS Cut Line= 4
2035247.91920333246784.3789177962035155.72657543246681.777444817
2035054.61208032246585.1238833152034876.17473601246429.734695977
#Sta/Elev= 30
       0 1743.28    73.1 1697.86    96.8 1685.59   110.6 1680.06   118.9 1675.02
   136.5 1675.17   140.5 1674.38   150.7 1670.33   168.3  1669.8   174.51667.647
   179.2 1666.91  192.731667.648   198.9  1669.1   262.4 1671.01   274.1 1669.08
   289.1 1670.88   316.9 1672.51   335.5 1682.56   354.4 1687.53   367.5 1689.25
   378.8 1694.06   391.4  1696.5   433.8 1709.83   454.5 1719.87   470.4 1729.31
   480.6 1732.55   493.7 1741.91     503 1743.18     510 1747.61   514.4 1749.35
#Mann= 4 ,-1 , 0
       0      .1       0      90     .04       0   174.5    .045       0
  192.73      .1       0
#XS Ineff= 2 , 0
                          251.86         1677.84
Permanent Ineff=
       F       F
Bank Sta=174.5,192.73
XS Rating Curve= 0 ,0
Exp/Cntr(USF)=0,0
Exp/Cntr=0.3,0.1

Type RM Length L Ch R = 1 ,5421    ,136.9,141.4,146.3
XS GIS Cut Line= 4
2035312.60274064246750.1784268032035227.10151316246592.558772661
2035143.83075248246486.2398550092035003.31134383246338.285557017
#Sta/Elev= 30
       0 1749.02    49.8 1721.47      99 1692.11   117.7 1682.69   128.9 1675.13
   147.1 1674.43   149.5 1673.25     155 1669.17   159.9 1667.78   227.2 1665.51
  233.04 1663.99   244.1 1663.22   251.8 1663.99   260.1 1665.71   277.2 1666.82
   319.3 1666.46   346.4 1667.61     361 1670.16   365.8 1672.43   376.7 1680.28
   380.1  1681.3   391.7 1682.95   395.3 1685.62   403.9 1694.53   409.2 1698.66
   451.6 1724.41   486.7 1749.73   500.2 1761.07   513.5 1765.36   518.4 1770.18
#Mann= 5 ,-1 , 0
       0      .1       0      40     .04       0  179.32      .1       0
  233.04    .045       0   251.8      .1       0
#XS Ineff= 2 , 0
          188.25 1679.06   291.4         1677.18
Permanent Ineff=
       F       F
Bank Sta=233.04,251.8
XS Rating Curve= 0 ,0
Exp/Cntr(USF)=0,0
Exp/Cntr=0.3,0.1

Type RM Length L Ch R = 1 ,5280    ,171,169.6,167.4
XS GIS Cut Line= 4
2035386.20814517246709.2865353982035330.44647507 246524.90127961
2035273.94131604246387.3558267032035163.90495371246215.609882803
#Sta/Elev= 30
       0 1743.54    24.2 1729.98    65.1 1709.49   120.2 1686.68     127 1680.79
   130.5 1679.09   147.6 1679.49   157.9 1674.09   168.2 1671.15   178.5 1664.93
   188.8 1662.43   238.3 1662.22   245.61659.795   251.8 1658.53   258.71659.797
   273.7 1664.09   319.7  1661.6   341.3 1663.23   356.3 1667.44   382.7 1684.47
   395.7 1686.95   423.2 1709.69   468.1 1749.17   481.4 1759.55   493.1 1770.93
   496.6 1773.05   504.8    1775   524.2 1794.51   539.8 1807.13   545.3 1810.14
#Mann= 5 ,-1 , 0
       0      .1       0      90     .04       0  192.63      .1       0
   245.6    .045       0   258.7      .1       0
#XS Ineff= 2 , 0
                          272.49         1675.65
Permanent Ineff=
       F       F
Bank Sta=245.6,258.7
XS Rating Curve= 0 ,0
Exp/Cntr(USF)=0,0
Exp/Cntr=0.3,0.1

Type RM Length L Ch R = 1 ,5110    ,161.2,161.2,161.1
XS GIS Cut Line= 4
2035536.72640943246662.0836050692035502.52849478246525.291946483
2035445.01382015246382.2824852342035340.86562554246152.223786703
#Sta/Elev= 30
       0 1713.71    32.7    1701    42.9 1693.61    46.3 1692.51    63.2 1692.31
    76.7 1686.26     124 1675.55   165.7 1668.61   186.9 1660.46  209.271656.052
     222 1655.51  232.981656.052     240  1658.4   318.2 1656.12   332.6 1658.53
   352.1 1673.54   368.6 1676.83   379.4 1684.37   393.8 1689.97   411.3 1699.85
   435.1 1720.17   456.3 1734.29   469.4 1747.41   487.4 1760.76   501.8 1774.58
   505.4 1777.33   516.3  1781.6   519.9  1786.1   523.5 1792.24   547.7 1810.09
#Mann= 5 ,-1 , 0
       0      .1       0      40     .04       0     151      .1       0
  209.27    .045       0  232.98      .1       0
#XS Ineff= 2 , 0
                          242.41         1668.94
Permanent Ineff=
       F       F
Bank Sta=209.27,232.98
XS Rating Curve= 0 ,0
Exp/Cntr(USF)=0,0
Exp/Cntr=0.3,0.1

Type RM Length L Ch R = 1 ,4949    ,111.6,111,110.3
XS GIS Cut Line= 4
2035598.90443606246649.6479997432035648.64685736 246456.89611719
2035602.01333739246344.9756692562035459.00387614246128.907026717
#Sta/Elev= 30
       0 1693.15     6.4 1691.91    23.3 1691.39    33.5 1688.04   101.3 1679.49
   252.9 1656.75   256.3 1655.37  263.991650.141   267.1  1648.8   270.6 1648.72
  277.21 1650.14   284.9 1653.88   371.2  1653.3   376.5 1654.05   383.4 1657.21
   399.1 1659.98   404.3 1664.25   418.5 1679.52   447.8 1705.74   463.5 1716.77
   484.8 1734.59   507.3 1751.69     525 1767.39   528.9    1770   541.6 1775.44
   544.7  1777.9   548.7 1783.71   552.5 1787.51   562.9 1795.67   579.4 1807.02
#Mann= 5 ,-1 , 0
       0      .1       0      30     .04       0     130      .1       0
  263.99    .045       0  277.21      .1       0
#XS Ineff= 2 , 0
                          293.12         1659.76
Permanent Ineff=
       F       F
Bank Sta=263.99,277.21
XS Rating Curve= 0 ,0
Exp/Cntr(USF)=0,0
Exp/Cntr=0.3,0.1

Type RM Length L Ch R = 1 ,4838    ,167.9,166.9,164.2
XS GIS Cut Line= 4
2035828.96313459246652.756901074 2035751.2406013246404.044794554
2035678.18142001 246259.480882642035553.82536675246104.035816065
#Sta/Elev= 30
       0 1690.98    16.6 1690.43    20.1 1689.11    26.9 1683.11    33.8 1679.49
    54.4 1674.31    78.5 1671.16     140 1666.64   218.6 1662.44     268 1657.26
   323.2 1653.04   326.4  1652.1  331.481648.507   334.2 1647.59  354.781648.506
   367.3 1650.49     382 1650.21   411.4 1653.84   418.7 1657.84   431.3 1658.08
   443.4 1661.57   451.8 1667.87   468.6  1683.8   496.4 1703.23   510.6 1714.89
   515.3 1718.01   524.4 1722.04   552.4 1738.71   594.1 1757.65   621.6 1775.27
#Mann= 4 ,-1 , 0
       0     .04       0     140      .1       0  331.48    .045       0
  354.78      .1       0
#XS Ineff= 2 , 0
                          380.09         1659.49
Permanent Ineff=
       F       F
Bank Sta=331.48,354.78
XS Rating Curve= 0 ,0
Exp/Cntr(USF)=0,0
Exp/Cntr=0.3,0.1

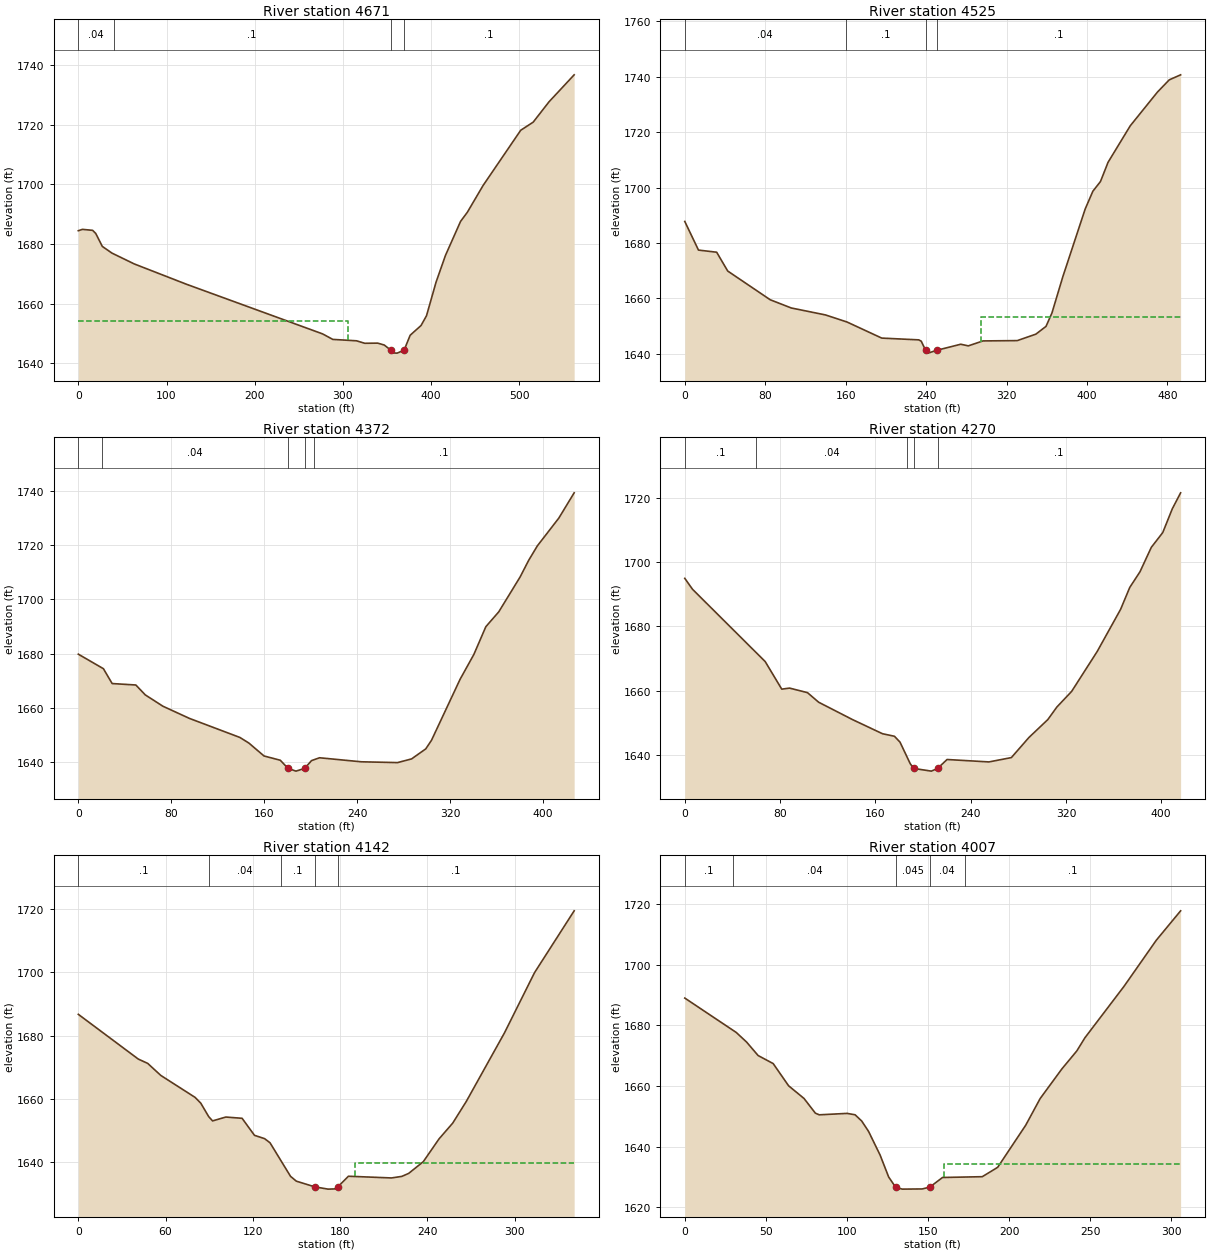
Type RM Length L Ch R = 1 ,4671    ,146.6,145.9,149.4
XS GIS Cut Line= 4
2036006.17051048246559.4898611292035898.91341455246344.975669256
2035825.85423326246201.9662080072035763.67620663246052.738944095
#Sta/Elev= 30
       0 1684.44     4.7 1684.89    16.2 1684.56    19.7 1683.54    27.2 1679.17
    38.2 1676.92    63.4  1673.3   122.5  1666.5   276.8 1649.86   288.5    1648
   315.4 1647.53   324.7  1646.7   339.4 1646.75   346.8 1646.12  354.25 1644.39
   357.8 1643.44   361.5  1643.4  369.331644.392   376.2  1649.4   388.5 1652.65
   394.7 1655.92   405.5 1667.15   416.2 1676.15   433.3 1687.54   441.1 1690.66
   458.8 1699.57   501.5  1718.1   515.7 1720.84   533.5 1727.61   562.1 1736.69
#Mann= 4 ,-1 , 0
       0     .04       0      40      .1       0  354.25    .045       0
  369.33      .1       0
#XS Ineff= 2 , 0
          305.16 1654.31
Permanent Ineff=
       F       F
Bank Sta=354.25,369.33
XS Rating Curve= 0 ,0
Exp/Cntr(USF)=0,0
Exp/Cntr=0.3,0.1

Type RM Length L Ch R = 1 ,4525    ,154.4,153.3,150.9
XS GIS Cut Line= 4
2036102.54645176246461.5594691872036015.49721448246295.233247952
2035964.20034251246189.5306026812035870.93330256246026.313282777
#Sta/Elev= 30
       0 1687.73    13.6  1677.4    31.7 1676.63    42.7 1669.83      85 1659.45
   105.9 1656.49     140 1653.97   161.3 1651.43   195.9 1645.61   232.8 1644.97
   235.2 1644.48   239.51641.236   241.9 1640.18  250.991641.239   274.5 1643.39
     282  1642.8   296.6 1644.59   330.7  1644.7   349.2 1647.03   359.3 1649.84
   365.2 1654.67   376.1 1667.86   398.3 1692.27   405.9 1698.65   413.5 1702.18
     421 1709.09   443.1 1722.29   470.1 1734.45   481.9 1738.89   493.2  1740.7
#Mann= 4 ,-1 , 0
       0     .04       0     160      .1       0   239.5    .045       0
  250.99      .1       0
#XS Ineff= 2 , 0
                          294.41         1653.18
Permanent Ineff=
       F       F
Bank Sta=239.5,250.99
XS Rating Curve= 0 ,0
Exp/Cntr(USF)=0,0
Exp/Cntr=0.3,0.1

Type RM Length L Ch R = 1 ,4372    ,106.6,102.1,97.4
XS GIS Cut Line= 4
2036219.13025169246334.0945145962036136.74436641246205.075109338
2036080.78414244246113.3625200592036004.61605982245965.689706813
#Sta/Elev= 30
       0 1679.77    21.6 1674.42    29.1 1668.95    49.5 1668.42    57.6 1664.78
    72.8  1660.6    95.6 1656.12     139 1649.11   146.8 1647.03   159.8 1642.28
   173.8 1640.71  180.441637.715   187.3  1636.7  194.781637.713   200.7 1640.58
   207.6 1641.62   243.4 1640.14   274.7 1639.84   286.8  1641.2     299  1644.9
   303.9 1648.03   328.5 1670.49   340.4 1679.68   350.7 1689.89   361.8 1695.35
   380.2 1708.21   387.6 1714.36     395 1719.64   413.5 1729.88   426.7 1739.19
#Mann= 5 ,-1 , 0
       0      .1       0      20     .04       0  180.44    .045       0
  194.78     .04       0  203.08      .1       0
Bank Sta=180.44,194.78
XS Rating Curve= 0 ,0
Exp/Cntr(USF)=0,0
Exp/Cntr=0.3,0.1

Type RM Length L Ch R = 1 ,4270    ,125.7,128.3,128.4
XS GIS Cut Line= 4
 2036318.6150943246278.1342906292036231.56585702246147.560434706
2036169.38783039246091.6002107392036079.22969177245940.818496161
#Sta/Elev= 30
       0 1694.89     6.5 1691.49    67.5 1669.03    81.4 1660.46      88 1660.78
     103 1659.37   112.4 1656.39   140.8    1651     166  1646.6     176 1645.82
   180.7 1643.99   189.3 1637.27  192.331635.809     207 1634.98  212.21 1635.81
   220.2 1638.59   255.4 1637.84   274.2 1639.19   288.9 1645.42   304.8    1651
   312.4  1654.9   324.8 1659.76   346.3 1672.19   365.9 1685.26   373.6 1692.07
   382.2 1696.95   391.7 1704.53   401.3 1709.12   409.3  1716.5   416.3 1721.47
#Mann= 5 ,-1 , 0
       0      .1       0      60     .04       0  186.93      .1       0
  192.33    .045       0  212.21      .1       0
Bank Sta=192.33,212.21
XS Rating Curve= 0 ,0
Exp/Cntr(USF)=0,0
Exp/Cntr=0.3,0.1

Type RM Length L Ch R = 1 ,4142    ,137.3,134.8,131.4
XS GIS Cut Line= 4
2036383.90202226246116.4714213912036287.52608098246046.521141432
 2036209.8035477245957.9174534842036144.51661973245877.086018865
#Sta/Elev= 30
       0 1686.78    41.2 1672.66    47.7 1671.29    56.7 1667.49    80.3 1660.55
    84.2 1658.73    89.6  1654.5    92.3 1653.13   101.4 1654.35   112.6 1653.95
   121.1 1648.58   128.1 1647.52   131.8 1646.22   145.9 1635.63   149.9  1634.1
  162.641632.302   171.7 1631.59   176.1 1631.65  178.421632.303   185.7 1635.66
   215.3 1635.12   222.4 1635.61   227.1 1636.55   237.2 1640.27     248 1647.45
   257.4 1652.43   266.7 1659.25   292.9 1680.85   313.7 1699.97   340.9 1719.46
#Mann= 5 ,-1 , 0
       0      .1       0      90     .04       0  139.09      .1       0
  162.64    .045       0  178.42      .1       0
#XS Ineff= 2 , 0
                          189.96         1639.87
Permanent Ineff=
       F       F
Bank Sta=162.64,178.42
XS Rating Curve= 0 ,0
Exp/Cntr(USF)=0,0
Exp/Cntr=0.3,0.1

Type RM Length L Ch R = 1 ,4007    ,93.5,92.2,91.2
XS GIS Cut Line= 4
2036425.87219024246012.3232267862036366.80306494245928.382890835
2036298.40723564  245875.53156822036212.91244903245796.254584246
#Sta/Elev= 30
       0 1688.96    31.7 1677.63    38.1 1674.45    45.2 1670.01    54.5 1667.35
      64 1660.03    73.5 1655.85    80.5    1651    82.9 1650.45   100.1 1650.92
     105 1650.46   109.1 1648.39   113.3 1644.98   120.4  1637.2   125.7 1629.94
  129.931626.612     134 1625.94   146.4    1626  151.061626.611   158.9 1629.78
   183.4 1630.04   192.9 1633.13   210.2 1647.03   219.1 1655.82   232.5  1665.6
   241.7 1671.53   246.7 1675.87   270.8 1692.83   290.7 1708.04   305.7 1717.74
#Mann= 5 ,-1 , 0
       0      .1       0      30     .04       0  129.93    .045       0
  151.06     .04       0  172.64      .1       0
#XS Ineff= 2 , 0
                          159.52         1634.33
Permanent Ineff=
       F       F
Bank Sta=129.93,151.06
XS Rating Curve= 0 ,0
Exp/Cntr(USF)=0,0
Exp/Cntr=0.3,0.1

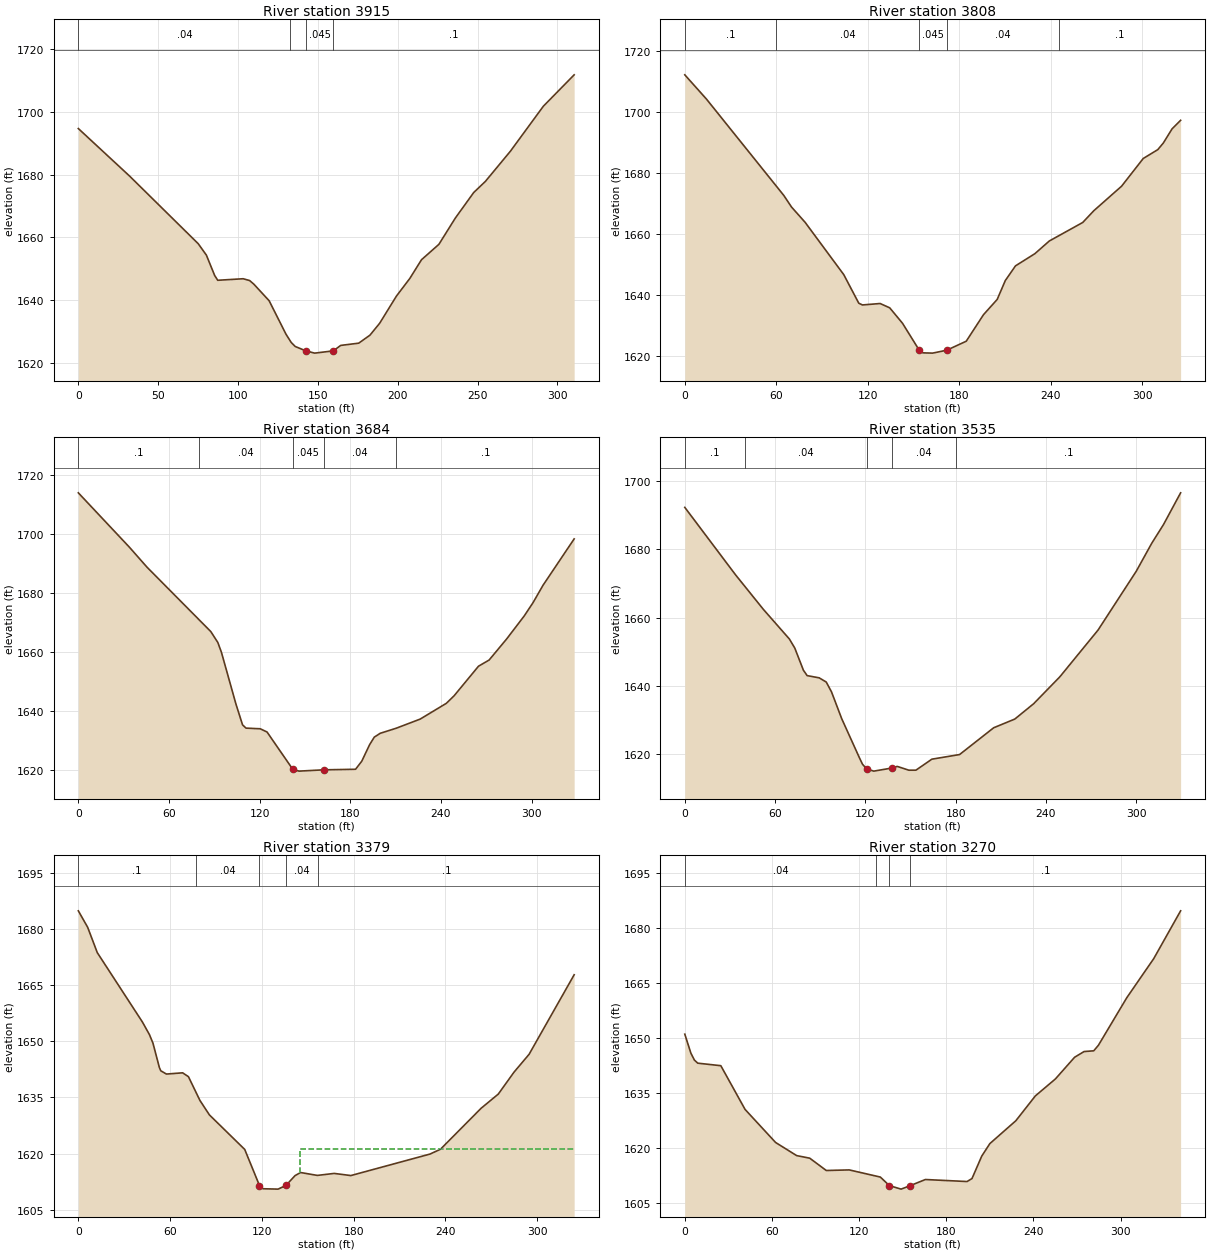
Type RM Length L Ch R = 1 ,3915    ,101.6,106.6,111.5
XS GIS Cut Line= 4
2036484.94131553245929.9373415012036425.87219024245858.432610876
2036343.48630495245797.8090349122036239.33811035245748.066613608
#Sta/Elev= 30
       0 1694.62      32 1679.56    75.1    1658    80.2 1654.37    85.4 1647.88
    87.3 1646.38   103.2 1646.87   107.3 1646.29   109.9 1645.15   119.5 1639.87
     130 1629.28   133.3 1626.62   135.8 1625.34  142.461623.938     148 1623.22
  159.661623.938   164.3 1625.67   175.6 1626.39   182.6 1628.92   188.7 1632.71
   199.2 1641.35   207.6 1646.97   214.9 1652.91   225.8 1657.81   236.1 1666.17
   247.6 1674.28   254.9 1677.81   270.6 1687.43   291.2 1701.71   310.5  1711.7
#Mann= 4 ,-1 , 0
       0     .04       0  132.75      .1       0  142.46    .045       0
  159.66      .1       0
Bank Sta=142.46,159.66
XS Rating Curve= 0 ,0
Exp/Cntr(USF)=0,0
Exp/Cntr=0.3,0.1

Type RM Length L Ch R = 1 ,3808    ,123.4,123.7,123.6
XS GIS Cut Line= 4
2036565.77275015245878.6404695312036497.37692086245802.472386909
 2036427.4266409245713.8686989622036351.25855828245634.591715008
#Sta/Elev= 30
       0 1712.07    14.2 1704.14    64.9 1672.64      70 1668.82    78.9 1663.83
   104.3 1646.68   114.1 1637.37   116.5 1636.79   128.1 1637.26   134.4 1635.85
   142.8  1630.8  153.771621.983   156.2 1621.12   162.5 1621.03   171.81621.981
   184.6 1624.93   195.9  1633.6   204.9  1638.6   210.2 1644.76   216.9 1649.58
   229.6 1653.56   239.1 1657.72     261 1663.77   268.3 1667.63   286.5 1675.65
   300.7 1684.71   310.2 1687.59   313.8 1689.72   319.6  1694.4   325.2 1697.19
#Mann= 5 ,-1 , 0
       0      .1       0      60     .04       0  153.77    .045       0
   171.8     .04       0  245.26      .1       0
Bank Sta=153.77,171.8
XS Rating Curve= 0 ,0
Exp/Cntr(USF)=0,0
Exp/Cntr=0.3,0.1

Type RM Length L Ch R = 1 ,3684    ,151.8,149.5,146.6
XS GIS Cut Line= 4
2036651.26753677245800.917936244 2036599.9706648245734.076557616
2036522.24813151245634.5917150082036441.41669689245549.096928392
#Sta/Elev= 30
       0 1713.98    33.8 1695.55    45.5 1688.75    87.7 1666.93    92.3 1663.28
    94.7 1659.95   104.3 1642.41   108.7 1635.31     111  1634.2   120.4 1633.98
   124.9 1632.89  141.911620.265   146.1 1619.62   162.4 1620.06   183.5 1620.25
   187.6 1622.97   192.8 1628.58   195.9 1631.14   199.8 1632.44   210.5 1634.18
   226.3 1637.27   243.6 1642.61   248.7 1645.15   264.9  1655.2   271.9 1657.28
   283.5 1664.42   295.1  1672.2     301 1676.76   307.6 1682.64   328.2 1698.36
#Mann= 5 ,-1 , 0
       0      .1       0      80     .04       0  141.91    .045       0
   162.4     .04       0   210.5      .1       0
Bank Sta=141.91,162.4
XS Rating Curve= 0 ,0
Exp/Cntr(USF)=0,0
Exp/Cntr=0.3,0.1

Type RM Length L Ch R = 1 ,3535    ,161.5,156.2,149.5
XS GIS Cut Line= 4
2036753.86128071245665.680728323 2036704.1188594245615.938307019
 2036595.3073128245508.6812110832036498.93137153245463.602141776
#Sta/Elev= 30
       0 1692.28    33.7 1672.55    52.2 1662.43    69.5 1653.75    73.1 1651.09
    78.8 1644.63    81.3 1643.03    89.3 1642.38      94 1641.15    97.5 1638.27
   104.3  1630.4   116.2 1618.83   118.1 1617.09  120.921615.703   125.6 1615.07
   137.41615.961   141.2 1616.45   148.9 1615.34   153.6 1615.35   164.2 1618.57
   182.6 1619.92   205.3 1627.77   219.3 1630.31   231.8 1634.79   249.2 1642.66
   274.6 1656.35     300 1673.57   310.3 1681.77   318.1 1687.23   329.5 1696.54
#Mann= 5 ,-1 , 0
       0      .1       0      40     .04       0  120.92    .045       0
   137.4     .04       0  180.35      .1       0
Bank Sta=120.92,137.4
XS Rating Curve= 0 ,0
Exp/Cntr(USF)=0,0
Exp/Cntr=0.3,0.1

Type RM Length L Ch R = 1 ,3379    ,108.4,108.6,106.4
XS GIS Cut Line= 4
2036859.56392598245528.8890697372036803.60370201245476.037747102
2036711.89111273245430.9586777952036573.54500348245387.434059154
#Sta/Elev= 30
       0 1684.78     6.1 1680.39    12.4 1673.62    41.9 1655.12    46.5 1651.75
    48.8 1649.48      53 1642.96    53.9 1642.11    57.6 1641.23    68.2 1641.56
      72 1640.53    79.5  1634.2    85.7 1630.34   108.8 1621.12  118.441611.495
   120.8 1610.63   130.6 1610.53  135.731611.499   141.7 1614.13   145.3 1614.96
   156.3 1614.19   167.3 1614.72   178.2 1614.15   229.9 1619.88   236.8 1621.17
   263.3 1632.08   274.6 1635.89   284.9 1641.75   294.7 1646.48   324.2 1667.72
#Mann= 5 ,-1 , 0
       0      .1       0   76.97     .04       0  118.44    .045       0
  135.73     .04       0  156.97      .1       0
#XS Ineff= 2 , 0
                          144.91         1621.29
Permanent Ineff=
       F       F
Bank Sta=118.44,135.73
XS Rating Curve= 0 ,0
Exp/Cntr(USF)=0,0
Exp/Cntr=0.3,0.1

Type RM Length L Ch R = 1 ,3270    ,78,81.4,92.3
XS GIS Cut Line= 4
2036906.19744595245435.6220297932036828.47491266245370.335101831
2036755.41573137245339.2460885162036598.41621413245306.602624535
#Sta/Elev= 30
       0 1651.13     4.2 1645.94     6.6 1644.07     8.9 1643.22    24.8 1642.53
    41.5  1630.6    62.5 1621.59      77 1618.01      86 1617.31    97.4 1613.95
   113.2 1614.11   134.6 1612.16  140.841609.825   148.9 1608.87  155.191609.825
   165.6 1611.49   194.3 1610.94   197.7 1611.76   204.4 1617.87     210 1621.29
   227.9 1627.53   241.3 1634.29   255.1 1638.91   268.3 1644.82   274.8 1646.38
   281.5 1646.59   284.7 1648.09   304.3  1661.1   322.8 1671.73   341.3 1684.76
#Mann= 4 ,-1 , 0
       0     .04       0   131.5      .1       0  140.84    .045       0
  155.19      .1       0
Bank Sta=140.84,155.19
XS Rating Curve= 0 ,0
Exp/Cntr(USF)=0,0
Exp/Cntr=0.3,0.1

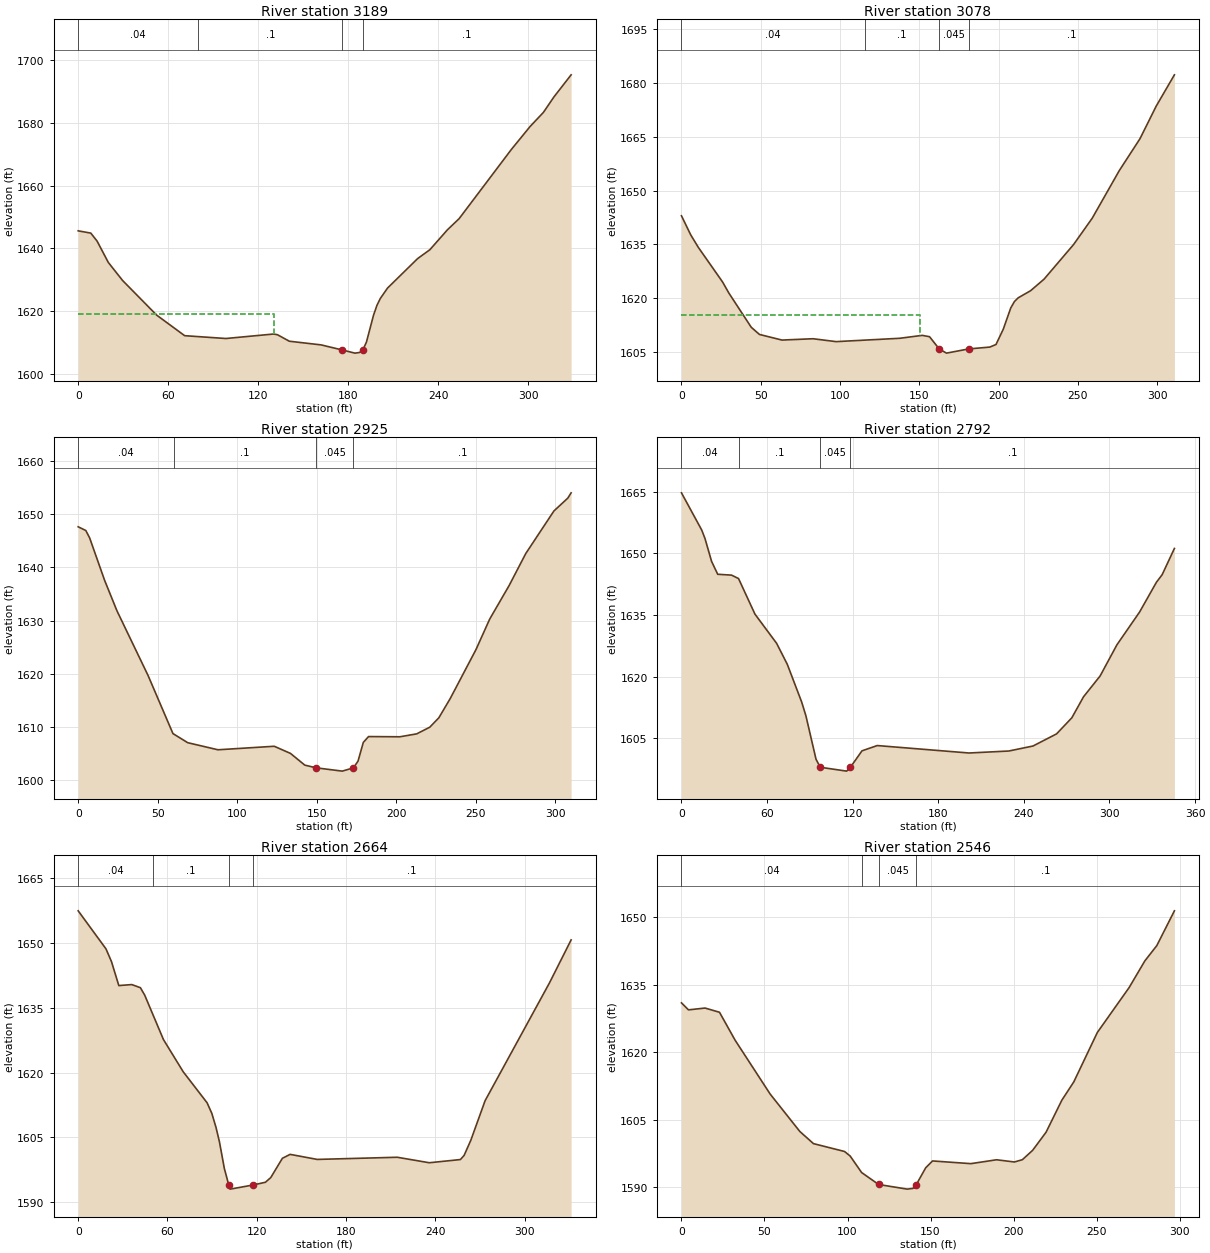
Type RM Length L Ch R = 1 ,3189    ,113.4,110.6,107
XS GIS Cut Line= 4
 2036945.0587126245392.0974111522036834.69271533 245305.04817387
2036789.61364602  245253.75130192036722.77226739245154.266459292
#Sta/Elev= 30
       0 1645.58     8.4 1644.86    12.6 1642.31    20.1 1635.48    29.6 1629.73
    52.3 1618.68      71  1612.1    98.5  1611.2   130.3 1612.63   132.9  1612.4
   140.8 1610.33     162 1609.16   176.21607.527   184.5 1606.53   187.6 1606.73
  189.791607.529   192.2 1610.04   196.9 1618.57   199.2 1621.77   201.5 1624.01
   206.3 1627.31   226.3  1636.7   234.5 1639.55   246.3 1645.95     254 1649.46
   288.9  1671.6   301.4 1678.93   310.2 1683.39   317.2 1688.32   328.7  1695.4
#Mann= 4 ,-1 , 0
       0     .04       0      80      .1       0   176.2    .045       0
  189.79      .1       0
#XS Ineff= 2 , 0
          130.87 1619.02
Permanent Ineff=
       F       F
Bank Sta=176.2,189.79
XS Rating Curve= 0 ,0
Exp/Cntr(USF)=0,0
Exp/Cntr=0.3,0.1

Type RM Length L Ch R = 1 ,3078    ,140,152.7,171.5
XS GIS Cut Line= 4
2036993.24668323245343.9094405132036937.28645927 245242.87014724
2036870.44508064245186.9099232732036800.49480068245104.524037988
#Sta/Elev= 30
       0 1642.94     5.8 1637.64    10.6 1634.13    25.9 1624.46    29.9 1621.34
      44 1611.79    49.2 1609.78    63.4 1608.22      83 1608.59    97.5 1607.78
   137.7 1608.72   151.8 1609.53   156.4 1609.16   162.51605.741   167.1 1604.57
  181.071605.742   194.4 1606.26   198.3 1606.98   202.9 1611.25   207.6 1617.18
   209.9 1618.96   212.3 1620.02   220.1    1622   228.6 1625.23   247.2 1634.89
     259 1642.28     276 1655.53   289.1 1664.48   299.3 1673.56   310.8 1682.32
#Mann= 4 ,-1 , 0
       0     .04       0   115.5      .1       0   162.5    .045       0
  181.07      .1       0
#XS Ineff= 2 , 0
          150.43 1615.29
Permanent Ineff=
       F       F
Bank Sta=162.5,181.07
XS Rating Curve= 0 ,0
Exp/Cntr(USF)=0,0
Exp/Cntr=0.3,0.1

Type RM Length L Ch R = 1 ,2925    ,139.9,133.4,127.4
XS GIS Cut Line= 4
2037095.84042717245292.6125685442037036.77130187245200.899979264
2037028.99904855245115.4051926482036957.49431792245025.247054035
#Sta/Elev= 30
       0 1647.61     4.8 1646.91     7.2 1645.53    16.6 1637.57    24.4 1631.82
      44 1619.65    59.6 1608.77    68.9 1607.06    87.9 1605.73   123.3 1606.39
   133.5 1605.05   142.5 1602.85  149.561602.343   166.1 1601.72  173.131602.344
     176 1603.61   179.3 1607.11   182.6 1608.21   202.3 1608.17   212.9 1608.72
   221.1 1609.97   226.8 1611.73     234 1615.37   250.2 1624.57   258.8 1630.28
     271 1636.57   281.5  1642.6   299.2 1650.59   307.9 1652.99     310 1653.99
#Mann= 4 ,-1 , 0
       0     .04       0      60      .1       0  149.56    .045       0
  173.13      .1       0
Bank Sta=149.56,173.13
XS Rating Curve= 0 ,0
Exp/Cntr(USF)=0,0
Exp/Cntr=0.3,0.1

Type RM Length L Ch R = 1 ,2792    ,139.9,128.3,116.4
XS GIS Cut Line= 4
2037218.64202977245255.3057525662037187.55301645245221.107837919
2037144.02839781245120.0685446452037038.32575254244963.069027405
#Sta/Elev= 30
       0 1664.74    14.2 1655.68    16.5 1653.61    21.1 1648.07    25.4 1644.93
    35.1 1644.72      40 1643.89    51.5 1635.24    66.7 1628.13    74.2 1623.01
    84.2  1613.9    87.2 1610.54    94.3 1599.95   97.251597.995   115.8 1597.05
  118.421597.993   126.5 1601.98   137.2 1603.27   201.5 1601.46   229.4 1601.94
   246.4 1603.16   262.9 1606.11   273.6 1610.02   281.8 1615.13   293.4 1620.18
   305.2 1627.77   321.1 1635.75   332.9 1642.99   336.9 1644.82   345.5 1651.21
#Mann= 4 ,-1 , 0
       0     .04       0      40      .1       0   97.25    .045       0
  118.42      .1       0
Bank Sta=97.25,118.42
XS Rating Curve= 0 ,0
Exp/Cntr(USF)=0,0
Exp/Cntr=0.3,0.1

Type RM Length L Ch R = 1 ,2664    ,123.6,117.7,114.9
XS GIS Cut Line= 4
 2037330.5624777245141.8308539662037274.60225373245093.642883328
2037192.21636845245040.7915606922037083.40482185244924.207760761
#Sta/Elev= 30
       0 1657.45    18.7 1648.63    22.4 1645.66    27.3 1640.14      36 1640.37
    41.8 1639.65    44.7 1637.92    57.3 1627.63    70.6 1620.16    86.6    1613
    89.8 1610.54    92.6 1607.29    94.9 1603.98    98.2 1597.79  101.161593.968
   102.1    1593  117.691593.969   125.8 1594.59   129.4 1595.68   137.2 1600.14
   142.4 1601.05   160.6 1599.88   214.4 1600.38   235.9 1599.11   256.8 1599.85
   259.3 1600.81   263.8 1604.31   273.4 1613.48   316.7 1640.79   331.2 1650.72
#Mann= 4 ,-1 , 0
       0     .04       0      50      .1       0  101.16    .045       0
  117.69      .1       0
Bank Sta=101.16,117.69
XS Rating Curve= 0 ,0
Exp/Cntr(USF)=0,0
Exp/Cntr=0.3,0.1

Type RM Length L Ch R = 1 ,2546    ,96.4,103.3,108.4
XS GIS Cut Line= 4
2037380.30489901245023.6926033692037308.80016838244970.841280734
2037231.07763509244945.9700700822037123.82053916244879.128691454
#Sta/Elev= 30
       0 1630.93     4.2 1629.38    14.2 1629.78    22.9 1628.85    32.3 1622.66
    53.4 1610.72    71.3 1602.41    79.5 1599.72    98.2 1597.98   101.6 1596.97
   108.5 1593.31  118.741590.658     136 1589.63   139.5  1589.8  141.451590.655
   147.1 1594.36   151.2 1595.88   174.3 1595.28   189.8 1596.14   200.5 1595.65
   205.3 1596.15   211.5 1598.23   219.6 1602.25   229.1 1609.35   236.3 1613.41
   250.5 1624.38   269.6 1634.31   279.1 1640.24   286.3 1643.63   296.9 1651.34
#Mann= 4 ,-1 , 0
       0     .04       0  108.92      .1       0  118.74    .045       0
  141.45      .1       0
Bank Sta=118.74,141.45
XS Rating Curve= 0 ,0
Exp/Cntr(USF)=0,0
Exp/Cntr=0.3,0.1