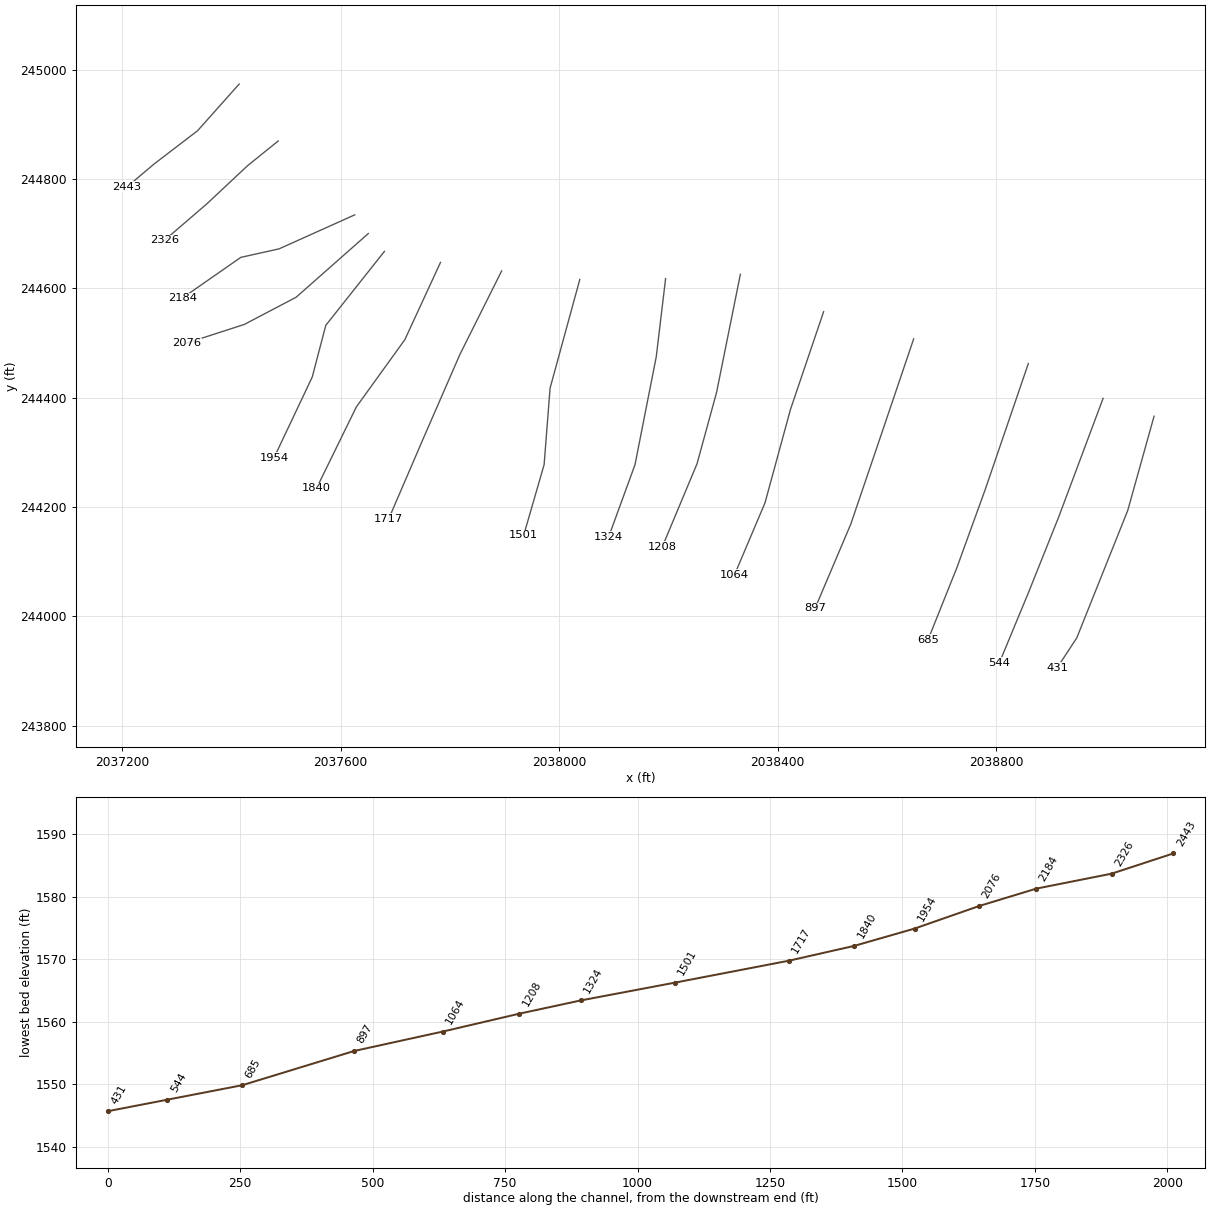
HEC-RAS study BOONECK.prj: BOONECK

--- BOONECK.g01 (geometry) --- (continued)

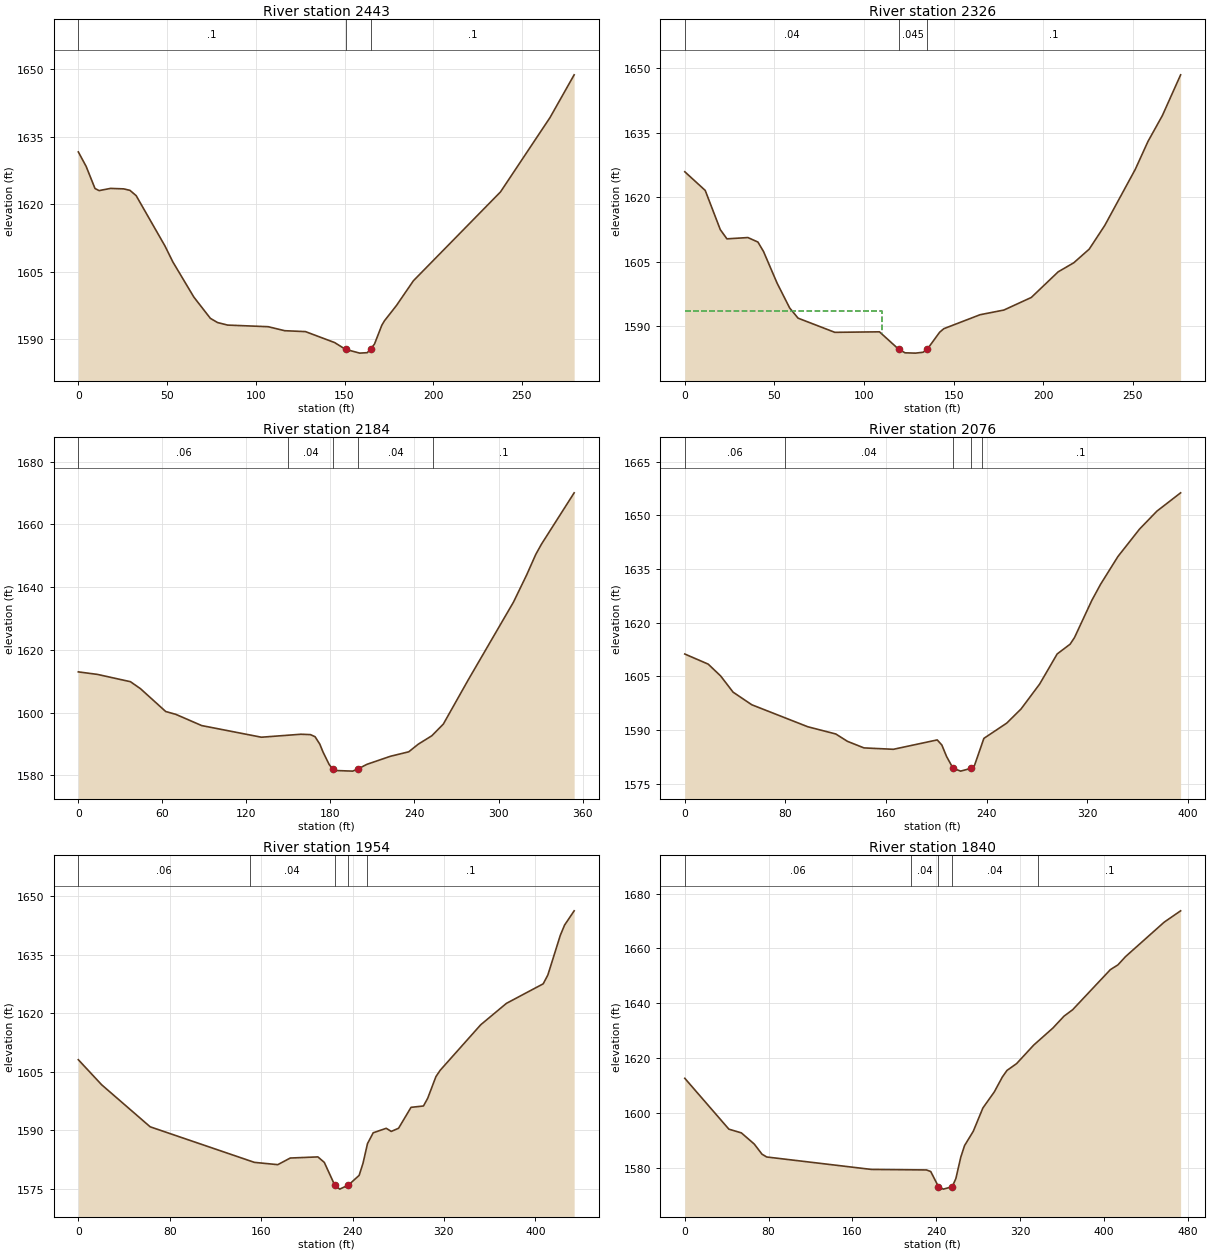
Type RM Length L Ch R = 1 ,2443    ,113.6,116.7,116.8
XS GIS Cut Line= 4
2037414.50281365244973.9501820652037338.33473103244888.455395449
2037259.05774708244827.8318194852037209.31532577244785.861651509
#Sta/Elev= 30
       0 1631.66     4.4 1628.45     9.4 1623.53    11.7 1623.07    18.2 1623.56
    25.6 1623.45    29.1 1623.12    32.6 1621.94    48.8 1610.78    53.3  1607.2
    65.1 1599.41    74.4 1594.69    78.4 1593.76    84.1 1593.19     107 1592.83
   116.3 1591.94     128 1591.74   144.4 1589.31  150.551587.807   158.6 1586.96
   162.8 1587.06  164.661587.805   166.9 1588.99     171 1593.14   172.5 1594.14
   179.3 1597.56   188.8 1603.03   237.9 1622.78   265.8  1639.3   279.4 1648.79
#Mann= 3 ,-1 , 0
       0      .1       0  150.55    .045       0  164.66      .1       0
Bank Sta=150.55,164.66
XS Rating Curve= 0 ,0
Exp/Cntr(USF)=0,0
Exp/Cntr=0.3,0.1

Type RM Length L Ch R = 1 ,2326    ,149.9,142.4,130
XS GIS Cut Line= 4
2037486.00754428 244869.801987462037430.04732031244824.722918153
2037355.43368835244754.7726381942037277.71115507244687.931259567
#Sta/Elev= 30
       0 1625.95    11.4  1621.6    19.8 1612.48    23.5 1610.33    35.2 1610.63
    40.8 1609.58    43.9  1607.4    51.5 1600.01    58.5 1594.24    63.2 1591.86
    83.7 1588.56   108.6 1588.68  119.361584.606   122.9 1583.79   128.7 1583.72
   132.9 1583.92  135.211584.604   142.2  1588.6   144.5 1589.41   164.7 1592.66
     178 1593.75   193.3 1596.68   208.3 1602.65     217 1604.76   225.6 1607.93
   234.3 1613.46   251.3 1626.51   258.4 1633.02   266.4 1639.02   276.6 1648.52
#Mann= 3 ,-1 , 0
       0     .04       0  119.36    .045       0  135.21      .1       0
#XS Ineff= 2 , 0
          110.03 1593.59
Permanent Ineff=
       F       F
Bank Sta=119.36,135.21
XS Rating Curve= 0 ,0
Exp/Cntr(USF)=0,0
Exp/Cntr=0.3,0.1

Type RM Length L Ch R = 1 ,2184    ,103.3,108.1,112.6
XS GIS Cut Line= 4
2037625.90810419 244734.564779542037487.56199494 244672.38675291
2037417.61171498244656.8422462522037310.35461905244582.228614296
#Sta/Elev= 30
       0 1612.96    13.7 1612.15    37.2 1609.83    44.4 1607.59    62.4 1600.32
    69.6 1599.42    88.1 1595.84   130.7 1592.13     159 1593.08   165.7 1592.96
     169  1592.3   172.4 1589.93   174.7 1587.41   179.1 1583.42  181.551582.047
   182.5 1581.53   195.9 1581.32  199.771582.046     206 1583.48   222.8 1586.05
   235.9 1587.48   242.7 1589.91   252.4  1592.6   260.6 1596.32   278.3 1610.35
   310.7 1635.22   320.1 1643.88   326.6 1650.41   330.6 1653.63     354 1670.04
#Mann= 5 ,-1 , 0
       0     .06       0     150     .04       0  181.55    .045       0
  199.77     .04       0  253.33      .1       0
Bank Sta=181.55,199.77
XS Rating Curve= 0 ,0
Exp/Cntr(USF)=0,0
Exp/Cntr=0.3,0.1

Type RM Length L Ch R = 1 ,2076    ,108.1,121.2,135.2
XS GIS Cut Line= 4
2037650.77931485244700.3668648932037518.65100826244583.783064962
2037423.82951765244534.0406436582037318.12687238244499.842729011
#Sta/Elev= 30
       0 1611.25    18.6 1608.43    28.5 1605.13    38.4  1600.6    53.3 1597.07
    97.9 1590.92   120.1 1588.91   129.4 1586.85   142.5 1585.02   165.9 1584.63
   200.8 1587.25   204.5  1585.8   208.2 1582.64  213.351579.338   219.4 1578.53
  228.021579.339   230.5 1580.18   237.9 1587.68   256.1 1591.95   267.5 1595.91
   282.3 1602.88   296.2 1611.27   306.5    1614     310 1615.86   323.8 1626.26
   330.7 1630.72   344.5 1638.48   361.7 1646.15   375.5 1651.16   394.4 1656.29
#Mann= 5 ,-1 , 0
       0     .06       0      80     .04       0  213.35    .045       0
  228.02     .04       0  236.21      .1       0
Bank Sta=213.35,228.02
XS Rating Curve= 0 ,0
Exp/Cntr(USF)=0,0
Exp/Cntr=0.3,0.1

Type RM Length L Ch R = 1 ,1954    ,120.5,114.4,108.4
XS GIS Cut Line= 4
 2037680.3138775244667.7234009122037573.05678156244532.486192992
2037548.18557091244437.6647023822037478.23529095244289.991889135
#Sta/Elev= 30
       0 1608.11    20.4 1601.69    62.9 1590.91   154.1  1581.8   174.6 1581.21
   185.5 1582.91   209.7  1583.2   215.3 1581.79  224.431575.969   228.8 1574.94
  236.361575.967   245.8 1578.47   249.2 1581.59   253.1  1586.6   258.1 1589.38
   269.5 1590.53   273.9 1589.73   280.3 1590.54   291.2  1595.9   302.1 1596.25
   305.8 1598.23     313 1603.77   316.7 1605.39   352.2 1617.06   374.7 1622.55
   406.9 1627.56     411 1629.84   421.9 1640.01   425.6 1642.61     434 1646.27
#Mann= 5 ,-1 , 0
       0     .06       0     150     .04       0  224.43    .045       0
  236.36     .04       0  252.61      .1       0
Bank Sta=224.43,236.36
XS Rating Curve= 0 ,0
Exp/Cntr(USF)=0,0
Exp/Cntr=0.3,0.1

Type RM Length L Ch R = 1 ,1840    ,119.5,123.4,126.6
XS GIS Cut Line= 4
2037782.90762143244647.5155422582037717.62069347244506.060531675
2037629.01700553 244383.258929082037555.95782424244234.031665168
#Sta/Elev= 30
       0 1612.61    42.1 1594.04      54 1592.69    66.3 1588.62    73.7 1584.92
    78.2 1583.89   178.1 1579.35   230.7 1579.16   234.8 1578.59  242.221573.045
   246.9 1572.16  255.321573.045   258.8    1576   263.5 1583.82   267.1 1588.05
   275.4 1593.25   284.6 1601.77   295.5 1607.64   303.2 1613.09   307.6 1615.48
   316.8 1617.97   333.1 1624.72   351.4 1630.93   362.1  1635.3   370.3 1637.63
   406.3 1652.26   413.6 1654.02   420.8 1657.02   457.7 1669.59   473.4 1673.73
#Mann= 5 ,-1 , 0
       0     .06       0  215.79     .04       0  242.22    .045       0
  255.32     .04       0  337.22      .1       0
Bank Sta=242.22,255.32
XS Rating Curve= 0 ,0
Exp/Cntr(USF)=0,0
Exp/Cntr=0.3,0.1

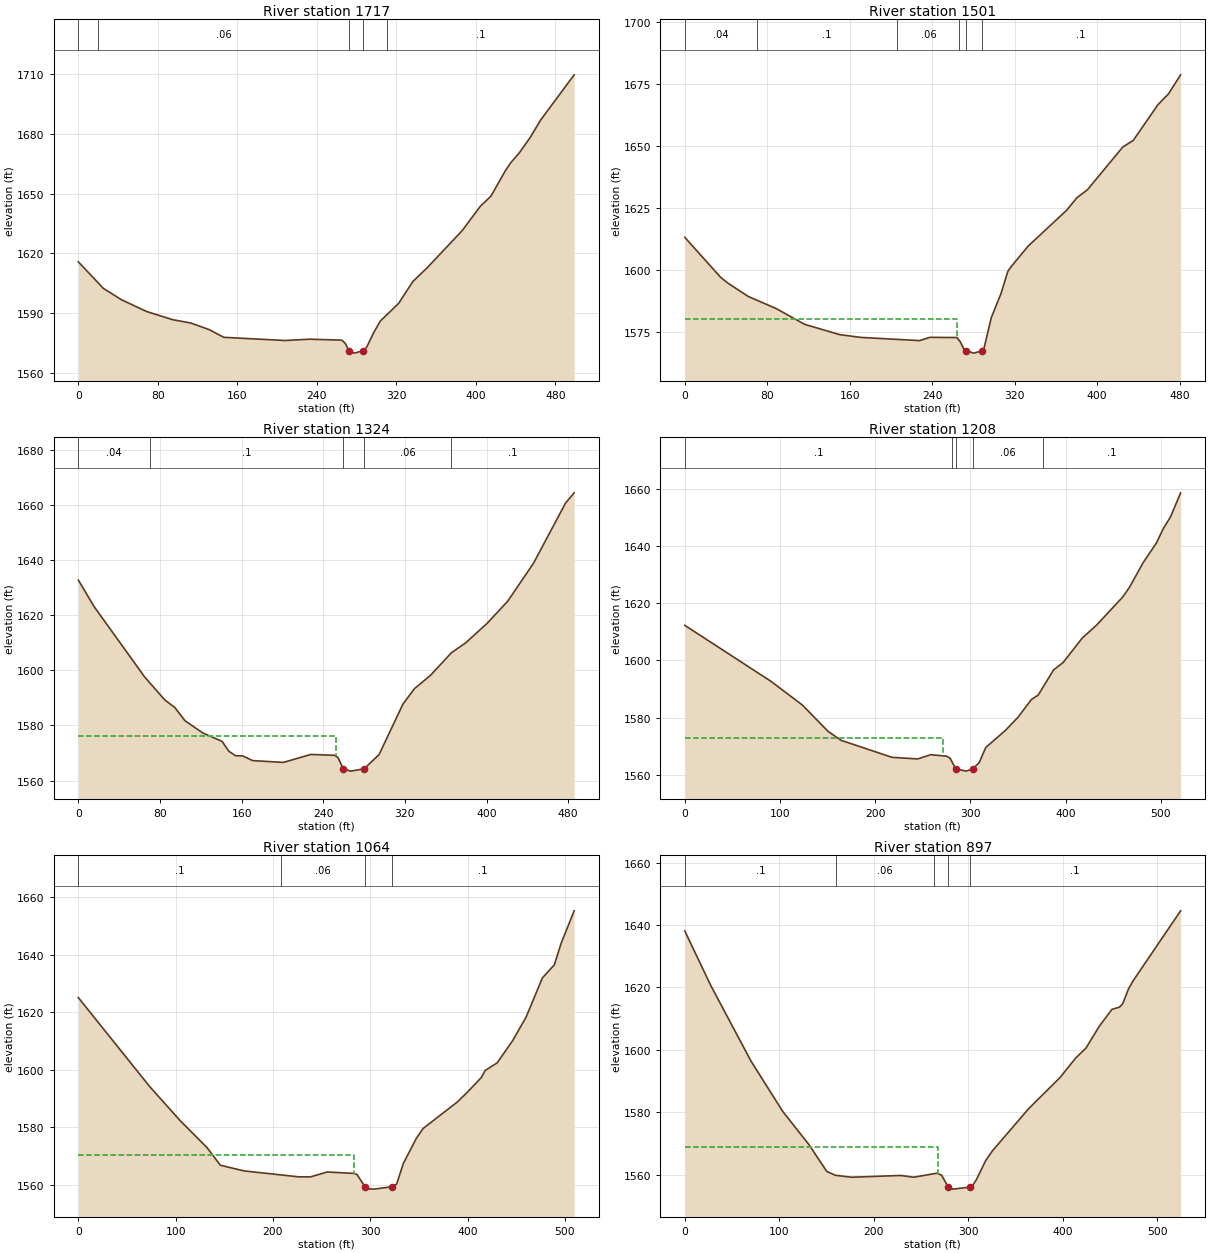
Type RM Length L Ch R = 1 ,1717    ,209.8,215.2,220.7
XS GIS Cut Line= 4
2037894.82806937  244631.97103562037818.65998675244479.634870357
2037750.26415745244322.6353531162037688.08613082244178.071441201
#Sta/Elev= 30
       0 1615.73    25.3 1602.32    43.6  1596.6      69 1590.67      95 1586.61
   113.3 1584.91   131.7 1581.61   146.4 1577.74   207.8 1576.14   232.8  1576.8
     265 1576.33   268.6  1574.7  272.26 1571.07   277.8 1569.79  286.87 1571.07
   290.1 1572.76   297.2 1580.11   303.8  1585.9   322.3 1594.82   336.6 1605.83
   350.9 1612.68   386.2  1631.4   404.5 1643.68   415.2 1648.76   429.5 1661.41
   434.9 1665.44   443.8  1670.6   454.5 1678.15   465.2 1687.08   498.9 1709.79
#Mann= 5 ,-1 , 0
       0      .1       0      20     .06       0  272.26    .045       0
  286.87     .06       0  310.32      .1       0
Bank Sta=272.26,286.87
XS Rating Curve= 0 ,0
Exp/Cntr(USF)=0,0
Exp/Cntr=0.3,0.1

Type RM Length L Ch R = 1 ,1501    ,179.4,177.3,174.4
XS GIS Cut Line= 4
2038037.83753062244616.4265289432037983.43175732244417.456843727
2037972.55060266244277.5562838092037935.24378668244148.536878552
#Sta/Elev= 30
       0 1613.02    34.6 1596.95    41.4 1594.64    61.6 1589.15      89 1584.19
   116.2  1577.9   150.2 1573.75   170.6 1572.63   227.7 1571.33   237.6 1572.65
   263.9 1572.57   267.2 1570.84   270.5 1568.07  272.981567.189   280.4 1566.28
  288.041567.193   290.2 1568.22   297.3 1580.63   306.7 1590.34   313.3 1599.27
   316.6 1601.21     333 1609.47   370.1 1623.84   380.3 1628.98   390.6 1632.26
   424.7 1649.42     435 1652.16   458.9 1666.55   469.1  1670.9   480.9  1678.6
#Mann= 6 ,-1 , 0
       0     .04       0      70      .1       0  206.27     .06       0
  266.27      .1       0  272.98    .045       0  288.04      .1       0
#XS Ineff= 2 , 0
          264.33 1580.24
Permanent Ineff=
       F       F
Bank Sta=272.98,288.04
XS Rating Curve= 0 ,0
Exp/Cntr(USF)=0,0
Exp/Cntr=0.3,0.1

Type RM Length L Ch R = 1 ,1324    ,118,116.5,115.6
XS GIS Cut Line= 4
2038194.83704786244617.9809796082038177.73809053 244474.97151836
2038138.87682389244277.5562838092038090.68885325244145.427977221
#Sta/Elev= 30
       0 1632.74    15.3  1623.2    64.9 1597.64    84.7 1589.26    94.6  1586.5
   104.5 1581.72   122.1 1577.26   140.9 1574.22   147.5 1570.65   154.2    1569
   160.9 1568.99   170.9 1567.25     201  1566.6   227.8 1569.49   251.2 1569.17
   254.5 1568.34   259.61564.296   266.9 1563.44  280.091564.295   294.7 1569.43
   318.1 1587.74   329.3 1593.31   345.2 1598.21   365.7 1606.41   379.7 1609.99
   400.7 1617.08   420.9 1625.12   446.1 1638.86   477.5 1660.69   485.9 1664.37
#Mann= 5 ,-1 , 0
       0     .04       0      70      .1       0   259.6    .045       0
  280.09     .06       0  365.23      .1       0
#XS Ineff= 2 , 0
          252.87 1576.24
Permanent Ineff=
       F       F
Bank Sta=259.6,280.09
XS Rating Curve= 0 ,0
Exp/Cntr(USF)=0,0
Exp/Cntr=0.3,0.1

Type RM Length L Ch R = 1 ,1208    ,143.5,143.9,146.3
XS GIS Cut Line= 4
2038331.62870644244625.753232937 2038288.1040878244409.684590398
2038252.35172249244279.110734475 2038188.6192452244126.774569232
#Sta/Elev= 30
       0 1612.29    90.4 1592.74   123.6  1584.4   150.6 1575.19     164 1572.11
   217.6 1566.14   244.7 1565.57   258.3 1567.05   275.3 1566.53   278.7 1565.82
  284.721562.113   295.7 1561.31  302.631562.113   309.3  1564.3   316.2 1569.58
   336.6 1575.48   350.2  1580.2   364.1 1586.34   371.3 1587.91   387.4 1596.69
   397.5  1599.3   417.5 1607.82   432.6 1612.36   460.2 1622.25   467.3 1625.66
   481.5 1634.18   495.3    1641   502.8 1646.17   510.3 1650.22   520.9 1658.62
#Mann= 5 ,-1 , 0
       0      .1       0  280.41     .06       0  284.72    .045       0
  302.63     .06       0  375.79      .1       0
#XS Ineff= 2 , 0
          271.63 1572.94
Permanent Ineff=
       F       F
Bank Sta=284.72,302.63
XS Rating Curve= 0 ,0
Exp/Cntr(USF)=0,0
Exp/Cntr=0.3,0.1

Type RM Length L Ch R = 1 ,1064    ,168.1,166.9,166
XS GIS Cut Line= 4
2038483.96487169244557.3574036442038423.34129572244378.595577083
2038376.70777575244207.6060038512038320.74755178244075.477697262
#Sta/Elev= 30
       0 1625.12    73.3 1594.16   104.5 1582.35   132.2 1572.92     146 1566.77
   170.3  1564.8   226.3 1562.74   238.7 1562.73   255.7 1564.43   282.9 1563.93
   286.3 1563.59  294.561559.281   296.5 1558.59   303.8 1558.46  322.131559.281
   327.1 1560.21   333.9 1567.36   347.5 1576.23   354.3 1579.57   389.3 1588.75
   400.4  1592.4   414.3 1597.38     418 1599.73   430.4 1602.41   446.4 1610.19
   460.1 1618.32   476.9 1631.99   489.1 1636.49   496.2 1644.08   509.5 1655.31
#Mann= 4 ,-1 , 0
       0      .1       0  208.76     .06       0  294.56    .045       0
  322.13      .1       0
#XS Ineff= 2 , 0
          283.67 1570.35
Permanent Ineff=
       F       F
Bank Sta=294.56,322.13
XS Rating Curve= 0 ,0
Exp/Cntr(USF)=0,0
Exp/Cntr=0.3,0.1

Type RM Length L Ch R = 1 ,897     ,211.8,211.5,211
XS GIS Cut Line= 4
2038648.73664226 244507.61498234 2038583.4497143244314.863099787
2038533.70729299244168.7447372072038468.42036503244014.854121298
#Sta/Elev= 30
       0 1638.09    27.7 1620.51    70.1 1596.39   103.7 1580.27   131.6 1569.56
   150.3 1561.05   159.3 1559.81   176.6 1559.17   228.6 1559.74   242.5 1559.18
   266.8 1560.47   271.9 1559.83  278.991556.007   284.1 1555.36  301.621556.007
   304.9 1556.63   308.3 1558.14   318.7 1564.56   325.7 1567.61   363.9 1581.08
   397.3 1591.12   413.8 1597.34   424.8 1600.57   438.8 1607.52   452.3 1612.98
   460.2 1613.67   463.7 1614.78   469.8 1619.53   474.8 1622.18     525 1644.55
#Mann= 5 ,-1 , 0
       0      .1       0     160     .06       0  263.51      .1       0
  278.99    .045       0  301.62      .1       0
#XS Ineff= 2 , 0
          268.19 1568.94
Permanent Ineff=
       F       F
Bank Sta=278.99,301.62
XS Rating Curve= 0 ,0
Exp/Cntr(USF)=0,0
Exp/Cntr=0.3,0.1

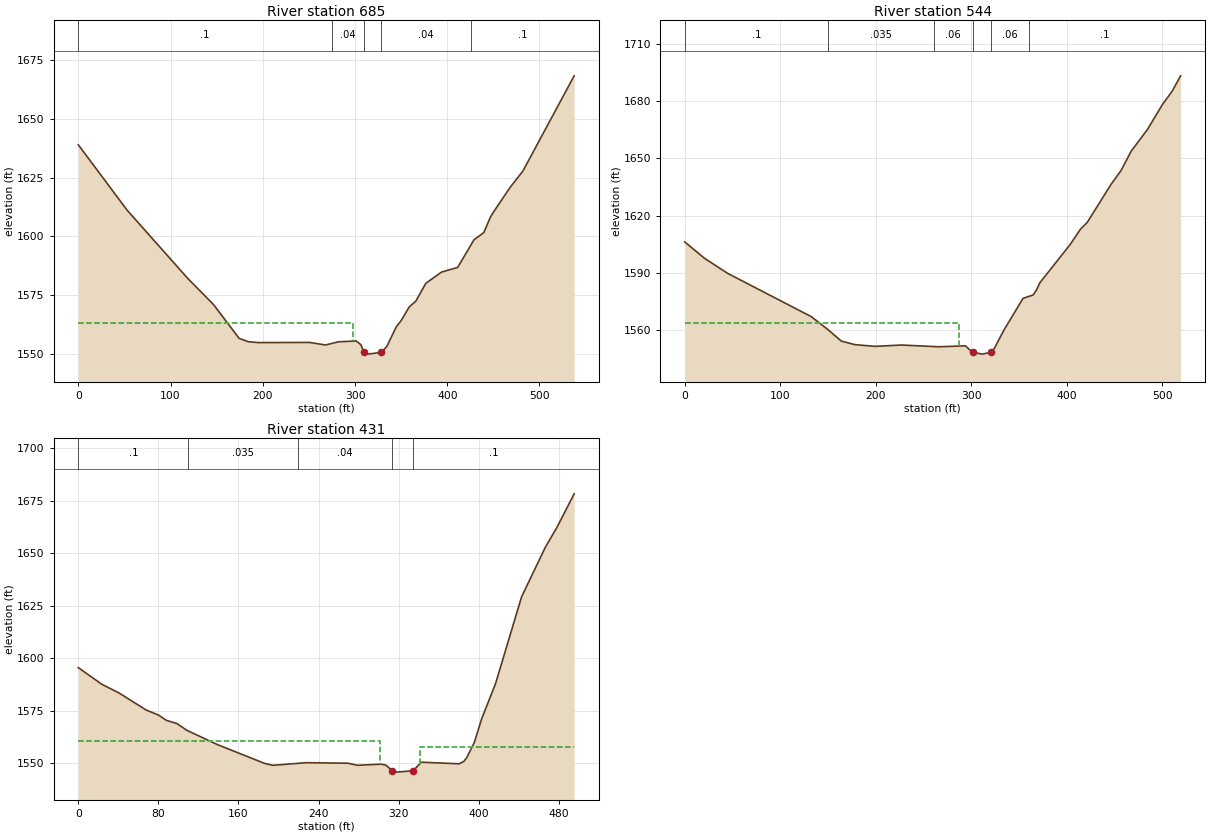
Type RM Length L Ch R = 1 ,685     ,141.7,141,140.4
XS GIS Cut Line= 4
2038858.58748213244462.5359130342038779.31049818244230.922763837
2038728.01362621244089.4677532542038675.16230357243957.339446665
#Sta/Elev= 30
       0 1638.96    52.9 1611.15   118.8 1582.04   146.5 1571.02   174.3  1556.6
   184.2 1555.17   195.1 1554.79   250.6 1554.86     268 1553.77     282 1555.12
   301.5 1555.47   306.4 1553.86  309.68  1550.6   313.4 1549.88  328.281550.606
   334.4 1553.09   344.8 1561.55   349.7 1563.96   358.8 1569.98   365.8 1572.36
   376.8 1580.03   393.7 1584.78   411.3 1586.78     429 1598.54   439.6 1601.59
   446.7 1608.09   450.3 1610.43   468.2 1620.86     482 1627.78   537.6 1668.32
#Mann= 5 ,-1 , 0
       0      .1       0  274.81     .04       0  309.68    .045       0
  328.28     .04       0  425.27      .1       0
#XS Ineff= 2 , 0
          297.42 1563.33
Permanent Ineff=
       F       F
Bank Sta=309.68,328.28
XS Rating Curve= 0 ,0
Exp/Cntr(USF)=0,0
Exp/Cntr=0.3,0.1

Type RM Length L Ch R = 1 ,544     ,113.1,112.9,113.2
XS GIS Cut Line= 4
2038995.37914072244398.803435738 2038914.5477061244182.734793199
2038858.58748213244042.834233281 2038805.7361595 243915.36927869
#Sta/Elev= 30
       0 1606.25    20.4 1597.81    44.9 1589.82   132.5 1567.18     150  1560.4
     164 1554.38   178.1 1552.54   199.1 1551.64   227.1 1552.33   265.9 1551.42
     294  1551.9  301.381548.548   311.7 1547.57  320.971548.549   324.1 1550.42
   334.4 1560.23   354.3 1576.74   364.9 1578.53   368.4 1581.13   371.9 1584.87
   403.9 1605.05   414.5 1612.96   421.6  1616.5   446.5 1636.38   457.1 1643.71
   467.7 1653.83   484.7 1665.14   500.3 1678.12   510.4 1685.03   519.4 1693.17
#Mann= 6 ,-1 , 0
       0      .1       0     150    .035       0  260.69     .06       0
  301.38    .045       0  320.97     .06       0  360.69      .1       0
#XS Ineff= 2 , 0
          287.11 1563.84
Permanent Ineff=
       F       F
Bank Sta=301.38,320.97
XS Rating Curve= 0 ,0
Exp/Cntr(USF)=0,0
Exp/Cntr=0.3,0.1

Type RM Length L Ch R = 1 ,431     ,109.9,112,113.8
XS GIS Cut Line= 4
2039088.64618066244366.1599717572039040.45821003244193.615947859
2038947.19117008243960.4483479972038911.43880477243906.042574695
#Sta/Elev= 30
       0 1595.49    23.4 1587.57    40.5 1583.46    67.7 1575.32      80 1572.93
      88 1570.37    98.4 1568.87   108.6 1565.59   139.3 1558.76   186.2 1549.87
   194.3 1548.96   227.7 1550.22   269.5 1549.96   279.1 1548.98   302.3 1549.51
   307.4 1549.03  313.681546.398     318 1545.72  334.52  1546.4   342.7 1550.44
   380.5 1549.69   385.1 1550.79   388.1 1552.61   395.7  1559.9   402.8 1570.86
   416.9 1587.92   442.9 1629.22   466.5 1652.68   478.5 1662.54   495.4 1678.24
#Mann= 5 ,-1 , 0
       0      .1       0     110    .035       0  219.15     .04       0
  313.68    .045       0  334.52      .1       0
#XS Ineff= 2 ,-1
       0  301.58 1560.31  340.97495.3774 1557.84
Permanent Ineff=
       F       F
Bank Sta=313.68,334.52
XS Rating Curve= 0 ,0
Exp/Cntr(USF)=0,0
Exp/Cntr=0.5,0.3