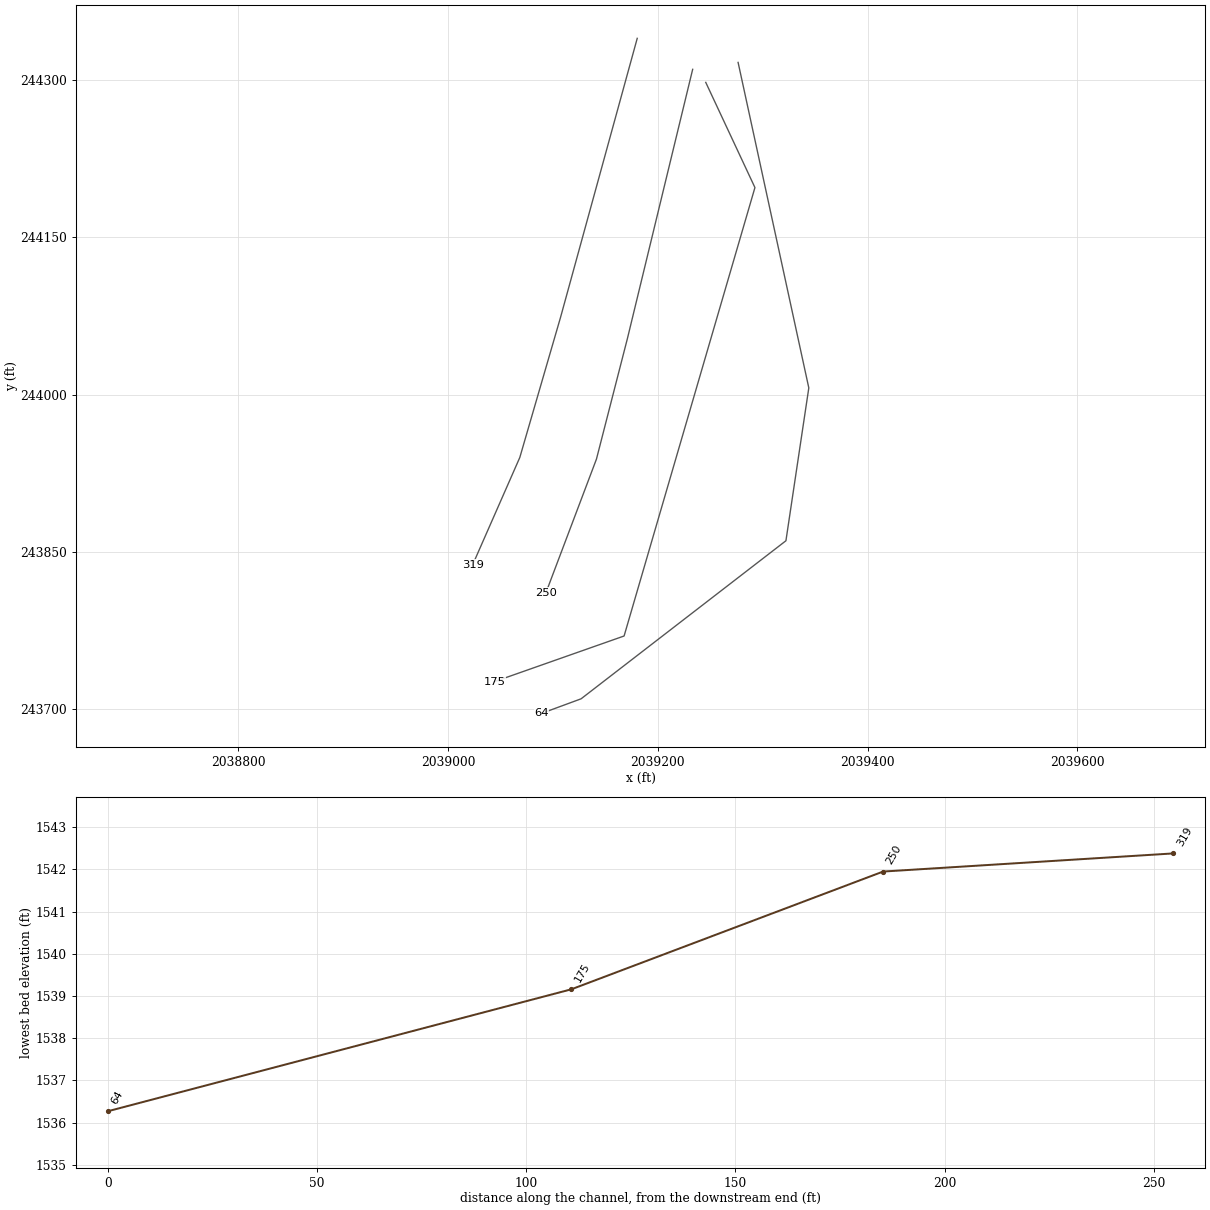
HEC-RAS study BOONECK.prj: BOONECK

--- BOONECK.g01 (geometry) --- (continued)

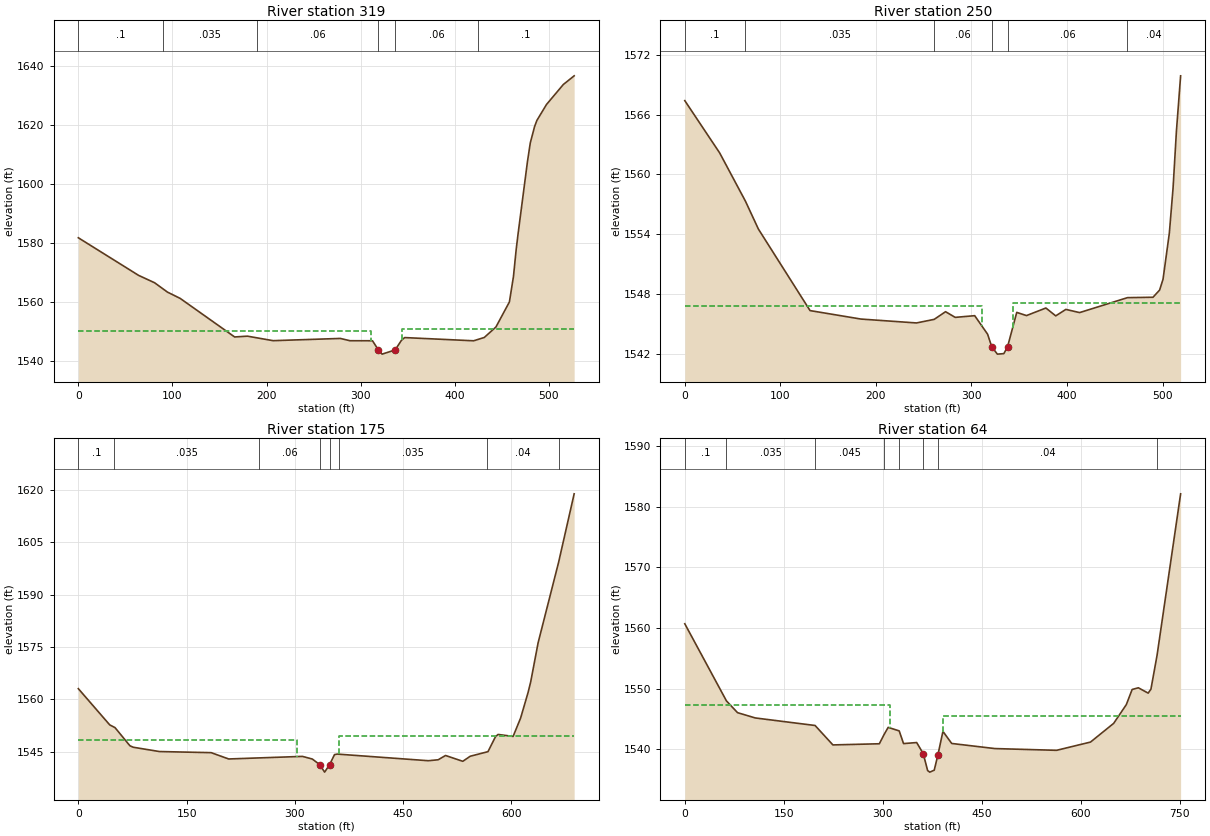
Type RM Length L Ch R = 1 ,319     ,70.1,69.4,71
XS GIS Cut Line= 4
2039180.35876994244339.7343104392039107.29958865244073.923246596
2039068.43832201243940.240489342 2039023.3592527243837.646745402
#Sta/Elev= 30
       0 1581.83    64.1 1569.07    81.1 1566.57    94.7 1563.41   108.3 1561.26
   166.1  1548.2   179.7 1548.47     207 1546.94   278.4  1547.7   288.7 1546.92
   312.6 1546.91  318.891543.792   322.8 1542.38  336.661543.792   343.3 1547.03
   346.8 1547.99   420.1  1546.9   431.4 1548.03   443.8 1551.59   458.1 1560.08
   462.4 1568.69   465.3 1577.89   467.4 1583.41   477.3 1607.71   480.3 1614.03
   484.8 1619.48   487.3 1621.62   497.5 1627.02   515.4  1633.8   526.9 1636.74
#Mann= 6 ,-1 , 0
       0      .1       0      90    .035       0     190     .06       0
  318.89    .045       0  336.66     .06       0  424.89      .1       0
#XS Ineff= 2 , 0
          311.17 1550.39  343.84         1550.78
Permanent Ineff=
       F       F
Bank Sta=318.89,336.66
XS Rating Curve= 0 ,0
Exp/Cntr(USF)=0,0
Exp/Cntr=0.5,0.3

Type RM Length L Ch R = 1 ,250     ,75.1,74.5,74
XS GIS Cut Line= 4
2039233.21009258 244310.199747792039171.03206595244053.715387942
 2039141.4975033243938.6860386762039093.30953266243811.221084085
#Sta/Elev= 30
       0  1567.4    36.5 1562.15    63.5  1557.3      77 1554.51   131.1 1546.32
   184.4 1545.47   242.5 1545.08     261 1545.44   272.9 1546.21     283 1545.64
   303.4 1545.81   316.9 1543.95  321.251542.688   327.1 1541.95   333.9    1542
  337.791542.686   347.4 1546.14   357.6 1545.82   377.9 1546.58   388.2 1545.79
   398.8 1546.44   413.2 1546.12   463.3 1547.62     490 1547.66   496.9 1548.38
   500.5 1549.47   507.1  1554.1     511 1558.64   514.5 1564.33   518.9 1569.89
#Mann= 6 ,-1 , 0
       0      .1       0    63.5    .035       0     261     .06       0
  321.25    .045       0  337.79     .06       0   463.3     .04       0
#XS Ineff= 2 , 0
       0  311.17  1546.8  342.98       0  1547.1
Permanent Ineff=
       F       F
Bank Sta=321.25,337.79
XS Rating Curve= 0 ,0
Exp/Cntr(USF)=0,0
Exp/Cntr=0.5,0.3

Type RM Length L Ch R = 1 ,175     ,108.5,110.8,114.2
XS GIS Cut Line= 4
2039245.67810485244297.7356565152039292.55310485244197.475239843
2039167.82980499243770.0415229052039044.28921595243726.555100963
#Sta/Elev= 30
       0 1563.08    43.5  1552.7    50.8 1551.92    71.5 1546.71    76.1 1546.29
   112.3 1545.06     184 1544.74   208.3 1542.93   310.5 1543.67   324.2 1542.91
   334.4 1541.31   341.2 1539.16   348.1 1541.31   354.9 1544.18   358.8 1544.33
   484.8 1542.43   498.5  1542.7   508.7 1543.93   532.6 1542.26   542.9 1543.71
   567.5 1545.03   577.9  1549.3   581.4 1549.96   602.3 1549.39   612.7 1554.64
   623.1 1562.01   626.7 1565.04     637 1576.26   665.3 1599.25   686.9 1618.92
#Mann= 8 ,-1 , 0
       0      .1       0      50    .035       0  250.68     .06       0
   334.4    .045       0   348.1     .06       0  360.68    .035       0
  565.94     .04       0  665.94      .1       0
#XS Ineff= 2 , 0
          302.74 1548.35  361.08         1549.53
Permanent Ineff=
       F       F
Bank Sta=334.4,348.1
XS Rating Curve= 0 ,0
Exp/Cntr(USF)=0,0
Exp/Cntr=0.3,0.1

Type RM Length L Ch R = 1 ,64      ,,,
XS GIS Cut Line= 5
2039276.50139489244316.7800166592039343.90376647244006.530865097
2039322.09711684243860.8227971112039126.82848152243710.158672391
2039089.16245034243696.281713536
#Sta/Elev= 30
       0  1560.7    63.2 1547.99      80 1546.06   106.9 1545.19   197.5 1543.95
   224.5 1540.75   294.9 1540.94   302.3  1542.5   308.3 1543.64     325 1543.06
   331.6 1540.97   351.5 1541.14   361.4 1539.33   368.1 1536.53   371.4 1536.27
   378.1 1536.59   383.6 1539.07   391.3 1542.98   404.6 1540.99   469.9 1540.15
   563.5 1539.86     615 1541.22   650.1  1544.3   669.3 1547.39   678.1 1549.88
   687.5 1550.16   702.4 1549.28   706.6 1549.93   715.9 1555.52   751.6  1582.1
#Mann= 8 ,-1 , 0
       0      .1       0    63.2    .035       0   197.5    .045       0
   302.3     .06       0     325     .04       0   361.4    .045       0
   383.6     .04       0   715.9      .1       0
#XS Ineff= 2 , 0
          310.55 1547.36  391.56         1545.47
Permanent Ineff=
       F       F
Bank Sta=361.4,383.6
XS Rating Curve= 0 ,0
Exp/Cntr(USF)=0,0
Exp/Cntr=0.3,0.1
LCMann Table=0

Chan Stop Cuts=-1
Use User Specified Reach Order=0
Composite Channel Slope=5